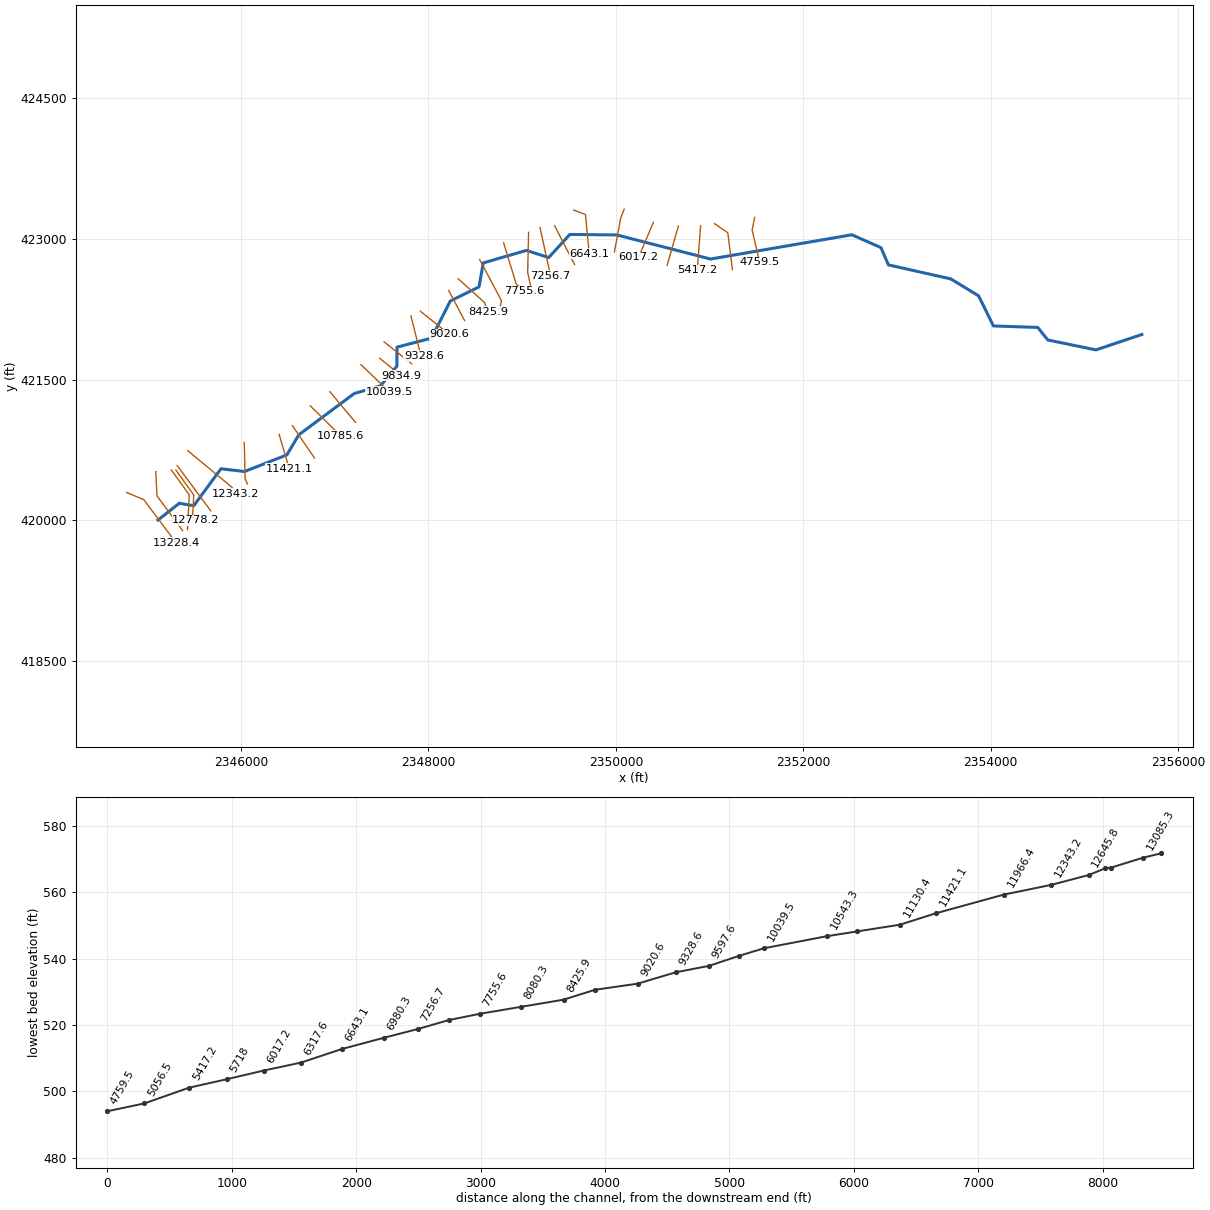
--- SWIMRUN.prj (project) ---

Proj Title=SWIMRUN
Current Plan=p01
Default Exp/Contr=0,0
English Units
Geom File=g01
Flow File=f01
Plan File=p01
BEGIN DESCRIPTION:
END DESCRIPTION:
DSS Export Rating Curves= 0
DSS Export Rating Curve Sorted= 0
DSS Export Volume Flow Curves= 0
DXF OffsetX= 0
DXF OffsetY= 0
DXF ScaleX= 0
DXF ScaleY= 0

--- SWIMRUN.p01 (plan) ---

Plan Title=Floodplain
Program Version=4.00
Geom File=g01
Flow File=f01
K Sum by GR=0
Std Step Tol=0.01
Critical Tol=0.01
Num of Std Step Trials=20
Max Error Tol=0.3
Flow Tol Ratio=0.001
Split Flow NTrial=30
Split Flow Tol=0.02
Split Flow Ratio=0.02
Log Output Level=0
Friction Slope Method=1
Unsteady Friction Slope Method=2
Unsteady Bridges Friction Slope Method=1
Global Log Level=0
CheckData=False
Run HTab=0
Run UNet=0
Run PostProcess=0
UNET Theta=0
UNET Theta Warmup=0
UNET ZTol=0
UNET ZSATol=0
UNET MxIter=0
UNET MaxInSteps=0
UNET DtIC=0
UNET DtMin=0
UNET MaxCRTS=0
UNET WFStab=0
UNET SFStab=0
UNET WFX=0
UNET SFX=0
UNET DSS MLevel=0
UNET DZMax Abort=0
UNET Convert EG Bridges=0
UNET Use Existing IB Tables=0
UNET Froude Limit=0
UNET Froude Power=0
Write IC File=0
Echo Input=False
Echo Output=False
Write Detailed=0

--- SWIMRUN.f01 (steady flow) ---

Flow Title=NFF Regression Equation
Program Version=4.00
Number of Profiles=1
Profile Names=P100yr
River Rch & RM=SWIMRUN,Main      ,13228.4
514.0941
River Rch & RM=SWIMRUN,Main      ,13085.3
514.0941
River Rch & RM=SWIMRUN,Main      ,12826.2
585.2393
River Rch & RM=SWIMRUN,Main      ,11130.4
642.5860
River Rch & RM=SWIMRUN,Main      ,9020.6
710.6882
River Rch & RM=SWIMRUN,Main      ,6317.6
784.3696
River Rch & RM=SWIMRUN,Main      ,6017.2
919.8764
River Rch & RM=SWIMRUN,Main      ,3917.7
995.6476
River Rch & RM=SWIMRUN,Main      ,1029.6
1093.190
River Rch & RM=SWIMRUN,Main      ,803.9
1278.001
River Rch & RM=SWIMRUN,Main      ,400.9
1278.888
Boundary for River Rch & Prof#=SWIMRUN,Main      ,1
Up Type=0
Dn Type=3
Dn Slope=0.011403

--- SWIMRUN.g01 (geometry) ---

Geom Title=USGS 10m DEM
Program Version=5.03

River Reach=SWIMRUN         ,Main
Reach XY= 30
      2345115.43      420003.121     2345342.861       420181.94
     2345497.375      420155.899     2345787.305      420549.996
     2346039.041      420520.482      2346490.43      420697.565
     2346618.902      420912.843      2347209.18      421352.079
     2347488.694      421433.676     2347664.041      421643.746
     2347665.777      421846.871     2348033.833      421942.357
     2348233.486       422338.19     2348540.778      422489.232
     2348585.472       422744.79     2349045.986      422878.121
     2349283.833      422801.732     2349509.528       423048.26
     2350009.995      423043.117     2351011.263      422786.107
     2352518.208      423044.787     2352828.972      422907.634
     2352908.833      422723.607     2353573.764      422574.301
     2353870.639      422393.746     2354028.625      422072.565
     2354500.847       422056.94     2354609.595      421922.822
     2355122.375      421817.357     2355611.883       421981.52

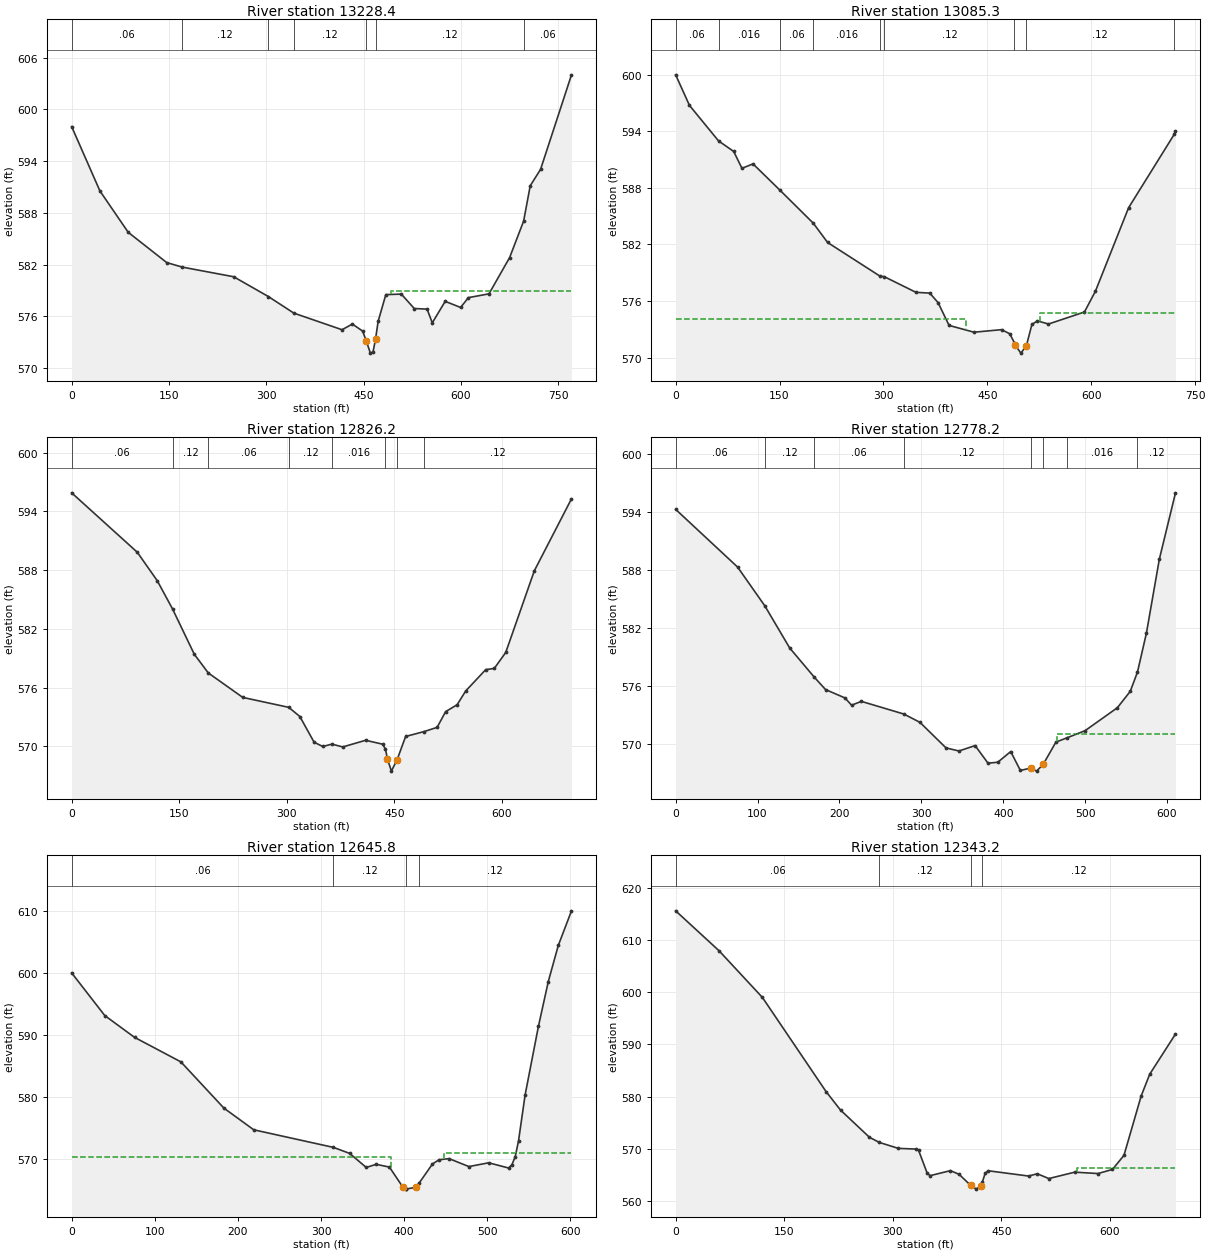
Type RM Length L Ch R = 1 ,13228.4 ,143.3,143,142.7
XS GIS Cut Line= 3
      2344780.15      420297.374     2344963.013      420221.086
     2345306.622      419763.289
#Sta/Elev= 30
       0     598    43.6  590.54    87.2  585.75   146.6  582.24  170.27581.7226
   249.8   580.6   303.3 578.304  342.57576.3838   416.8  574.46   432.7  575.12
   448.6   574.3   454.2  573.14   460.5  571.75   464.5  571.87   468.4  573.35
   472.4  575.42   484.3  578.53   508.2  578.59   528.1  576.92   547.9  576.85
   555.9  575.26   575.8  577.75   599.6  577.04   611.5  578.18   643.3  578.62
   675.1  582.82  696.71587.0488   706.9  591.15   722.8  593.04   770.5     604
#Mann= 7 ,-1 , 0
       0     .06       0  170.27     .12       0   303.3    .016       0
  342.57     .12       0   454.2    .045       0   468.4     .12       0
  696.71     .06       0
#XS Ineff= 2 , 0
                          492.98          578.95
Permanent Ineff=
       F       F
Bank Sta=454.2,468.4
XS Rating Curve= 0 ,0
Exp/Cntr=0.3,0.1

Type RM Length L Ch R = 1 ,13085.3 ,273.5,259.1,243.2
XS GIS Cut Line= 3
     2345091.515      420519.938     2345104.557      420261.023
      2345379.35      419889.006
#Sta/Elev= 30
       0     600    19.9  596.76   61.94592.9874    83.8  591.87    95.7  590.08
   111.7  590.55  150.86587.7399  198.89584.2437   219.4  582.21  294.49578.6639
  301.53578.5714     347  576.92   366.9  576.84   378.9  575.83   394.8  573.41
   430.7  572.69   470.6  572.96   482.5  572.52   488.9  571.59   490.5  571.28
   498.5  570.47   506.4  571.26   514.4  573.52   522.4  573.89   538.3  573.56
   590.2  574.83   606.1  577.04     654   585.9  719.88593.6866   721.7  593.99
#Mann= 9 ,-1 , 0
       0     .06       0   61.94    .016       0  150.86     .06       0
  198.89    .016       0  294.49     .06       0  301.53     .12       0
   488.9    .045       0   506.4     .12       0  719.88     .06       0
#XS Ineff= 2 , 0
           419.4   574.1  525.49          574.69
Permanent Ineff=
       F       F
Bank Sta=490.5,506.4
XS Rating Curve= 0 ,0
Exp/Cntr=0.3,0.1

Type RM Length L Ch R = 1 ,12826.2 ,77.9,48,48
XS GIS Cut Line= 3
      2345258.99      420536.064     2345449.395      420271.256
     2345429.939       419900.93
#Sta/Elev= 30
       0  595.89    91.5  589.82   119.3  586.92  140.69584.0276     171   579.4
  190.59577.4856   238.6  574.99  302.72573.9763   318.2  573.04   338.1  570.41
   350.1  569.98  363.05570.2173     378  569.93   409.9  570.61   433.8  570.21
   437.6  569.68  440.42568.7064   445.8  567.46   453.8  568.62   465.7     571
  491.75571.5075   509.6  571.93   521.5  573.54   537.5  574.24   549.5  575.65
   577.4  577.83   589.3  577.95   605.3  579.58   645.2  587.93     697  595.28
#Mann= 8 ,-1 , 0
       0     .06       0  140.69     .12       0  190.59     .06       0
  302.72     .12       0  363.05    .016       0   437.6    .045       0
   453.8    .016       0  491.75     .12       0
Bank Sta=440.42,453.8
XS Rating Curve= 0 ,0
Exp/Cntr=0.3,0.1

Type RM Length L Ch R = 1 ,12778.2 ,85,132.4,149.8
XS GIS Cut Line= 4
     2345306.733      420535.196     2345497.138      420270.388
     2345484.918      420037.788     2345520.129      420000.552
#Sta/Elev= 30
       0  594.29    75.6  588.33  108.84584.3236   139.2  579.97  169.28576.9482
     183  575.67   206.8   574.8   214.8  574.05   226.7  574.45  278.64573.1386
   298.3  572.28   330.1  569.64   345.9  569.32   365.6  569.88   381.4  568.06
   393.3  568.16   409.1  569.26   420.9  567.31   433.7  567.56   440.6  567.24
   448.7  567.93   464.3  570.24  478.26570.6964   499.9  571.42   539.3  573.79
   555.1  575.49  563.89577.4836   574.8   581.5   590.6  589.15   610.3     596
#Mann= 8 ,-1 , 0
       0     .06       0  108.84     .12       0  169.28     .06       0
  278.64     .12       0   433.7    .045       0   448.7     .12       0
  478.26    .016       0  563.89     .12       0
#XS Ineff= 2 , 0
                          465.22          571.03
Permanent Ineff=
       F       F
Bank Sta=433.7,448.7
XS Rating Curve= 0 ,0
Exp/Cntr=0.3,0.1

Type RM Length L Ch R = 1 ,12645.8 ,297.4,302.6,307.8
XS GIS Cut Line= 2
     2345320.743      420583.317     2345678.993      420100.537
#Sta/Elev= 30
       0  600.01    39.8  593.15    75.6  589.64   131.4  585.69   183.1  578.25
     219  574.76  314.77571.9292   334.4  570.96   354.3   568.7   366.3   569.2
   382.2  568.76   398.1  565.59   402.1  565.21   402.6  565.23   414.1  565.51
   417.6  566.12     434  569.26   441.9  569.94   453.9  570.12   477.8  568.84
   501.6  569.45   525.5  568.61   529.5  569.13   533.5  570.42   537.5  572.98
   545.4  580.36   561.4  591.39   573.3  598.62   585.3  604.42   601.2     610
#Mann= 4 ,-1 , 0
       0     .06       0  314.77     .12       0   402.6    .045       0
   417.6     .12       0
#XS Ineff= 2 , 0
          383.59  570.39  447.54             571
Permanent Ineff=
       F       F
Bank Sta=398.1,414.1
XS Rating Curve= 0 ,0
Exp/Cntr=0.3,0.1

Type RM Length L Ch R = 1 ,12343.2 ,393.3,376.8,358.4
XS GIS Cut Line= 3
     2345433.413      420742.881     2345907.195      420350.019
     2345940.414      420282.592
#Sta/Elev= 30
       0  615.65      60  607.98   119.9  599.02   207.8  580.96   227.8  577.41
   267.8  572.18  281.56571.1948   307.7  570.06   331.7  569.93   335.7  569.66
   347.7  565.24   351.7  564.83   379.7  565.79   391.7  565.07   407.6  562.96
   415.5  562.24  421.42562.8424   423.6  563.54   427.6  565.26   431.6  565.77
   487.6  564.75   499.6  565.19   515.6  564.27   551.5   565.5   583.5  565.23
   603.5  566.02   619.4  568.72   643.2  580.13     655   584.3   690.6  592.01
#Mann= 4 ,-1 , 0
       0     .06       0  281.56     .12       0   407.6    .045       0
   423.6     .12       0
#XS Ineff= 2 , 0
                          554.38          566.38
Permanent Ineff=
       F       F
Bank Sta=407.6,421.42
XS Rating Curve= 0 ,0
Exp/Cntr=0.3,0.1

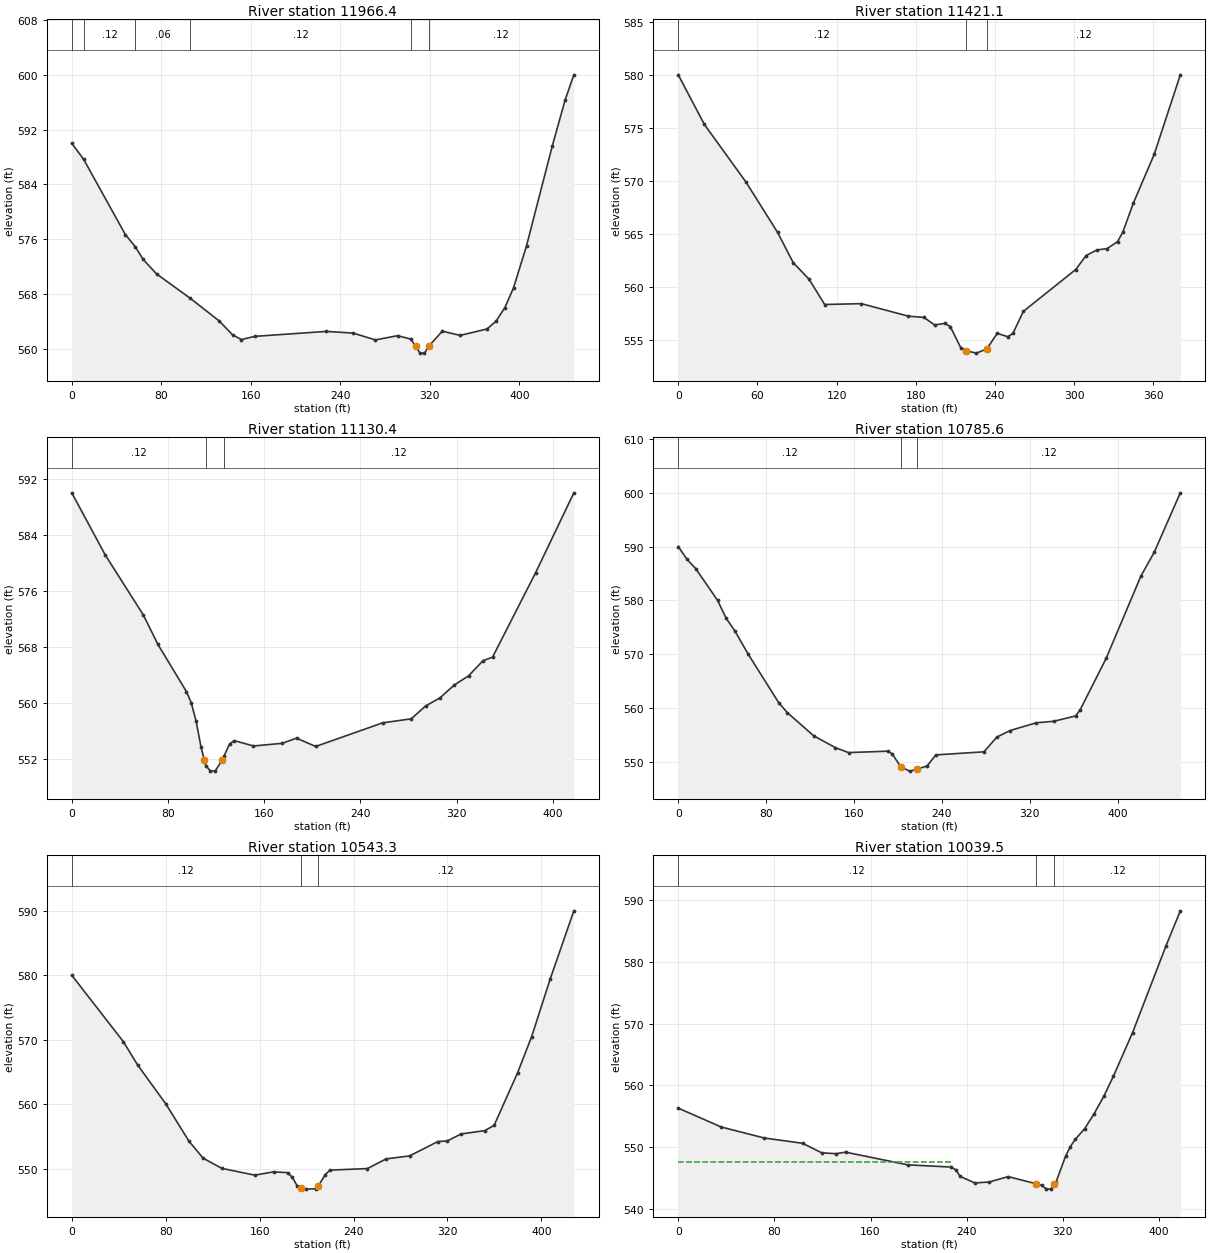
Type RM Length L Ch R = 1 ,11966.4 ,534.6,545.3,551.5
XS GIS Cut Line= 3
     2346036.114      420830.406     2346045.321      420439.429
     2346069.604      420387.047
#Sta/Elev= 30
       0     590    10.6 587.658    47.9  576.67   56.77574.8895    63.8  573.03
    75.8  570.92  105.79 567.371   131.7  564.06   143.7  562.03   151.6  561.33
   163.6   561.8   227.5  562.52   251.4  562.28   271.4  561.28   291.3   561.9
   303.3  561.39   307.3  560.32   311.3  559.35   315.3  559.35   319.2  560.37
   331.2  562.56   347.2  561.94   371.1  562.87   379.1  563.99   387.1  565.98
   394.9  568.89   406.5  575.03   429.6  589.65   441.1  596.37   448.8     600
#Mann= 6 ,-1 , 0
       0     .06       0    10.6     .12       0   56.77     .06       0
  105.79     .12       0   303.3    .045       0   319.2     .12       0
Bank Sta=307.3,319.2
XS Rating Curve= 0 ,0
Exp/Cntr=0.3,0.1

Type RM Length L Ch R = 1 ,11421.1 ,288.2,290.7,298
XS GIS Cut Line= 2
     2346407.936      420916.359     2346516.114      420551.475
#Sta/Elev= 30
       0     580    19.8  575.32    51.5  569.85    75.3  565.13    87.2  562.26
    99.1  560.72     111  558.32   138.8   558.4   174.4  557.22   186.3   557.1
   194.3  556.39   202.2  556.54   206.2  556.24   214.1  554.26     218  553.96
     226  553.73   233.9  554.12   241.8   555.6   249.8  555.28   253.7  555.59
   261.6  557.67   301.3  561.62   309.2  562.94   317.2  563.46   325.1   563.6
     333  564.25     337  565.14   344.9  567.86   360.8  572.49   380.6     580
#Mann= 3 ,-1 , 0
       0     .12       0     218    .045       0   233.9     .12       0
Bank Sta=218,233.9
XS Rating Curve= 0 ,0
Exp/Cntr=0.3,0.1

Type RM Length L Ch R = 1 ,11130.4 ,340.4,344.9,349.3
XS GIS Cut Line= 2
      2346549.97      421009.532     2346785.105      420664.537
#Sta/Elev= 30
       0     590    27.8  581.14    59.6  572.54    71.6  568.37    95.4  561.61
    99.4     560   103.4   557.4   107.4  553.78  110.23551.8498   111.6  551.06
   115.3  550.27   119.3   550.3  125.21551.8809   126.6  552.42   131.2  554.14
   135.2  554.62   151.1  553.86     175  554.24   186.9  554.98   202.8  553.79
   258.5  557.16   282.3  557.74   294.2  559.57   306.2  560.73   318.1  562.57
     330  563.88     342  566.04   349.9  566.54   385.7  578.59   417.5     590
#Mann= 3 ,-1 , 0
       0     .12       0   111.6    .045       0   126.6     .12       0
Bank Sta=110.23,125.21
XS Rating Curve= 0 ,0
Exp/Cntr=0.3,0.1

Type RM Length L Ch R = 1 ,10785.6 ,244.5,242.3,240
XS GIS Cut Line= 2
     2346740.928      421220.537     2347065.702      420898.949
#Sta/Elev= 30
       0     590       8  587.63    15.9  585.91    35.8     580    43.7  576.63
    51.7  574.27    63.6  570.01    91.4  560.98    99.4  559.09   123.2  554.82
   143.1  552.59     155  551.68   190.8  551.94   194.7  551.45   202.7  549.01
   210.6  548.23   217.7  548.61   226.5  549.19   234.5  551.25   278.2  551.82
   290.1  554.57     302  555.78   325.9  557.22   341.8   557.5   361.7   558.5
   365.6  559.55   389.5  569.21   421.3  584.59   433.2  588.92     457     600
#Mann= 3 ,-1 , 0
       0     .12       0   202.7    .045       0   217.7     .12       0
Bank Sta=202.7,217.7
XS Rating Curve= 0 ,0
Exp/Cntr=0.3,0.1

Type RM Length L Ch R = 1 ,10543.3 ,501.1,503.8,506.3
XS GIS Cut Line= 2
     2346948.452      421372.344     2347223.007      421044.359
#Sta/Elev= 30
       0     580      44  569.68      56   566.1      80  560.06    99.9  554.23
   111.9   551.6   127.9  550.02   155.9  548.97   171.9  549.48   183.9  549.36
   187.9  548.62   191.9  547.34   194.9  546.98   199.9   546.8   207.9  546.86
   209.9  547.25   215.9  549.04   219.9  549.75   251.8  549.99   267.8  551.49
   287.8  551.96   311.8  554.18   319.8  554.28   331.8  555.37   351.8  555.88
   359.8   556.7   379.8  564.87   391.8  570.49   407.7  579.49   427.7     590
#Mann= 3 ,-1 , 0
       0     .12       0   194.9    .045       0   209.9     .12       0
Bank Sta=194.9,209.9
XS Rating Curve= 0 ,0
Exp/Cntr=0.3,0.1

Type RM Length L Ch R = 1 ,10039.5 ,202.6,204.5,206.4
XS GIS Cut Line= 2
     2347281.789      421659.315     2347583.845      421370.748
#Sta/Elev= 30
       0   556.3    35.8  553.24    71.6  551.46   103.4  550.61   119.4  549.06
   131.3  548.92   139.2  549.17     191  547.11   226.8  546.76   230.8  546.33
   234.7  545.23   246.7  544.18   258.6  544.33   274.5  545.21     298  544.03
   302.4  543.77   306.3  543.18   310.3  543.21     313  543.97   314.3  544.34
   322.3  548.53   326.2  550.06   330.2  551.23   338.2  552.99   346.1  555.43
   354.1  558.24     362  561.46     378  568.54   405.8  582.59   417.7  588.26
#Mann= 3 ,-1 , 0
       0     .12       0     298    .045       0     313     .12       0
#XS Ineff= 2 , 0
          226.12  547.62
Permanent Ineff=
       F       F
Bank Sta=298,313
XS Rating Curve= 0 ,0
Exp/Cntr=0.3,0.1

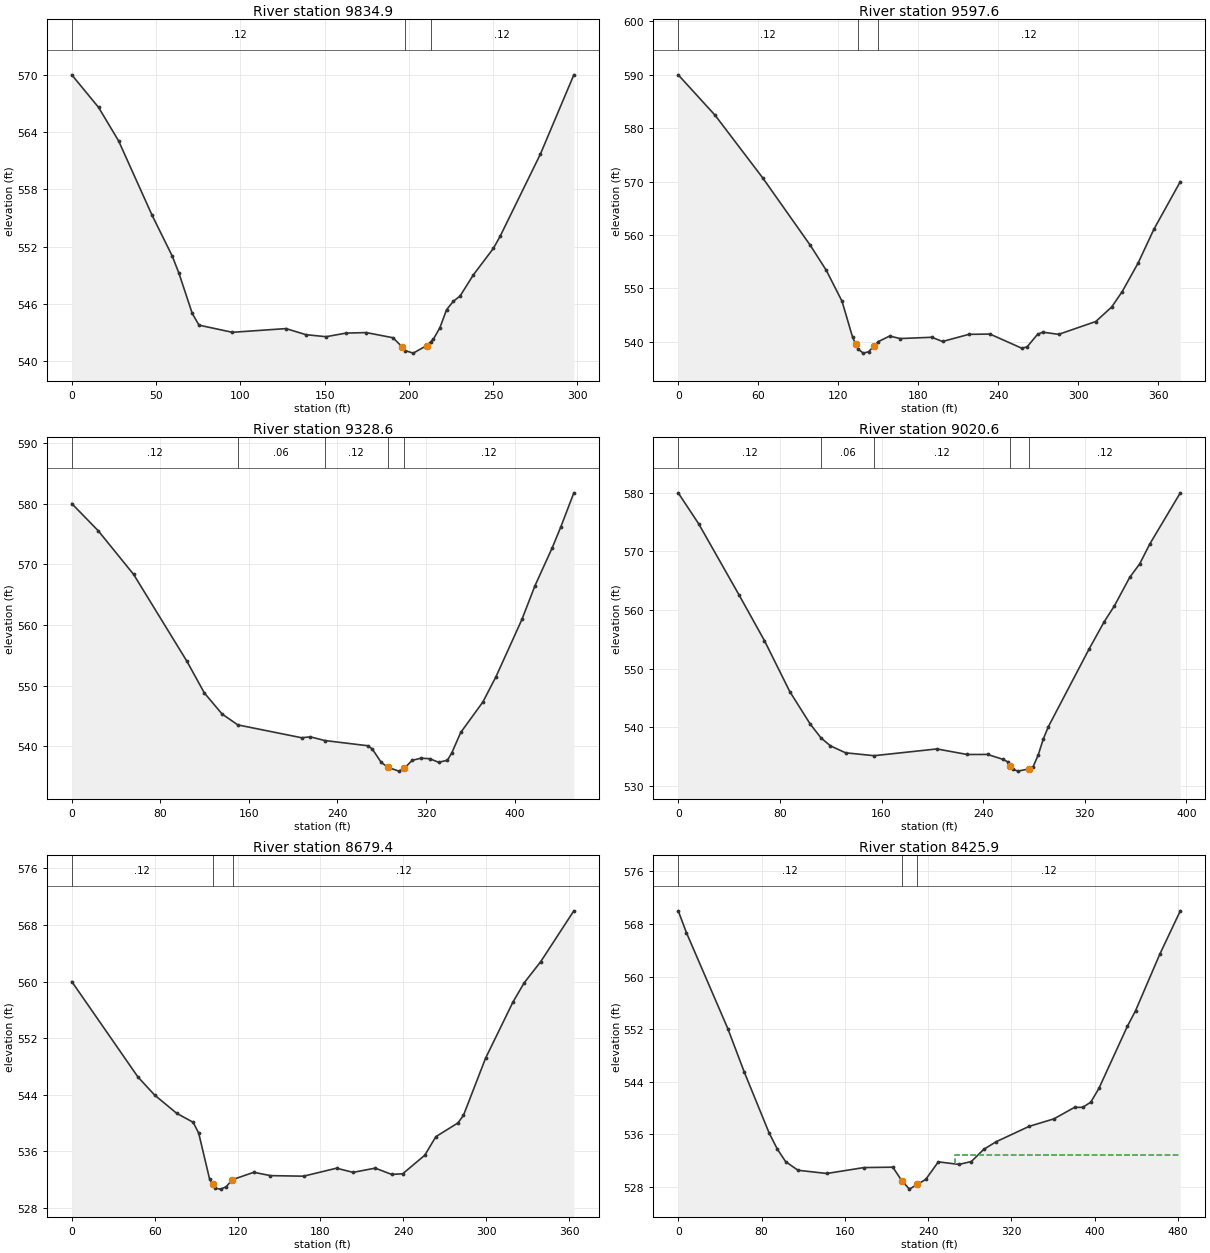
Type RM Length L Ch R = 1 ,9834.9  ,236.7,237.3,237.9
XS GIS Cut Line= 2
     2347481.428      421727.224     2347713.536      421540.537
#Sta/Elev= 30
       0     570    15.9  566.59    27.8  563.08    47.7  555.28    59.6  551.03
    63.6  549.22    71.5  545.01    75.5  543.79    95.3  543.04   127.1  543.43
     139  542.79   150.9  542.58   162.8  542.96   174.8  543.01   190.6  542.47
  196.21541.4836   197.9  541.12   202.6  540.86   210.5  541.64   212.9  542.04
   214.5  542.31   218.4  543.51   222.4  545.41   226.4  546.29   230.4  546.84
   238.3  549.06   250.2  551.84   254.2  553.11     278  561.68   297.9     570
#Mann= 3 ,-1 , 0
       0     .12       0   197.9    .045       0   212.9     .12       0
Bank Sta=196.21,210.5
XS Rating Curve= 0 ,0
Exp/Cntr=0.3,0.1

Type RM Length L Ch R = 1 ,9597.6  ,283.9,269,254.1
XS GIS Cut Line= 2
     2347528.114      421902.586     2347822.999      421668.537
#Sta/Elev= 30
       0     590    27.7  582.41    63.4  570.68    99.1  558.04     111  553.39
   122.8   547.6   130.8  540.81  132.96539.6303   135.1   538.6   138.7  537.87
   142.7  538.12   146.6  539.16   150.1  540.03   158.5  541.07   166.4   540.6
   190.2  540.84   198.2  540.05     218  541.39   233.8  541.44   257.6  538.79
   261.6  539.04   269.5  541.41   273.4  541.79   285.3  541.39   313.1  543.79
     325   546.5   332.9  549.39   344.8  554.72   356.7  561.08   376.5     570
#Mann= 3 ,-1 , 0
       0     .12       0   135.1    .045       0   150.1     .12       0
Bank Sta=132.96,146.6
XS Rating Curve= 0 ,0
Exp/Cntr=0.3,0.1

Type RM Length L Ch R = 1 ,9328.6  ,293.1,308,322.7
XS GIS Cut Line= 3
     2347814.783      422177.868     2347906.822      421809.829
     2347954.173      421752.644
#Sta/Elev= 30
       0  580.01      24  575.51    55.9  568.33   103.8  554.09   119.8   548.8
   135.8  545.33  150.01  543.54   207.7  541.42   215.6  541.57  228.45540.9648
   267.6   540.1   271.6  539.54   279.5  537.38   285.4  536.56   295.5  535.92
   300.4  536.38   307.5  537.69   315.5  538.06   323.5  537.96   331.4  537.38
   339.4  537.71   343.4  538.96   351.4  542.29   371.4  547.31   383.3   551.5
   406.7  560.92   418.4  566.44   434.1  572.74   441.9   576.2   453.6  581.78
#Mann= 5 ,-1 , 0
       0     .12       0  150.01     .06       0  228.45     .12       0
   285.4    .045       0   300.4     .12       0
Bank Sta=285.4,300.4
XS Rating Curve= 0 ,0
Exp/Cntr=0.3,0.1

Type RM Length L Ch R = 1 ,9020.6  ,351,341.3,331.6
XS GIS Cut Line= 2
     2347914.291      422230.107     2348223.176      421983.628
#Sta/Elev= 30
       0     580      16  574.75    47.9  562.56    67.9  554.75    87.8  546.07
   103.8  540.55  112.39 538.149   119.8   536.8   131.7  535.61  154.16535.1169
   203.6  536.27   227.5  535.32   243.5  535.33   255.5   534.5   259.5  534.05
   261.4  533.44   263.4   532.8   267.4  532.48   276.4  532.88   279.4  533.26
   283.4  535.27   287.4     538   291.4   540.1   323.3   553.3   335.3     558
   343.3   560.7   355.3  565.55   363.2  567.87   371.2  571.28   395.2  580.01
#Mann= 5 ,-1 , 0
       0     .12       0  112.39     .06       0  154.16     .12       0
   261.4    .045       0   276.4     .12       0
Bank Sta=261.4,276.4
XS Rating Curve= 0 ,0
Exp/Cntr=0.3,0.1

Type RM Length L Ch R = 1 ,8679.4  ,245.5,253.5,261.2
XS GIS Cut Line= 2
     2348216.494      422452.157     2348386.003      422130.648
#Sta/Elev= 30
       0     560    47.9  546.51    59.9  543.97    75.9  541.38    87.9   540.1
    91.9  538.56    99.8  532.06   101.9  531.38   103.8  530.77   107.8  530.65
   111.8  530.98   115.8   531.9   116.9  532.03   131.8  533.03   143.8  532.56
   167.8  532.48   191.7  533.61   203.7  533.02   219.7  533.62   231.6  532.73
   239.6  532.82   255.6  535.45   263.6  538.07   279.6  540.01   283.6  541.09
   299.6  549.17   319.5  557.13   327.5  559.81   339.5  562.81   363.5     570
#Mann= 3 ,-1 , 0
       0     .12       0   101.9    .045       0   116.9     .12       0
Bank Sta=101.9,115.8
XS Rating Curve= 0 ,0
Exp/Cntr=0.3,0.1

Type RM Length L Ch R = 1 ,8425.9  ,353.8,345.6,337.4
XS GIS Cut Line= 3
      2348318.65      422575.731     2348600.973      422320.535
     2348634.272      422224.537
#Sta/Elev= 30
       0     570     7.9  566.67    47.6  552.09    63.4  545.48    87.2  536.24
    95.1  533.77   103.1  531.85     115  530.53   142.7  530.04   178.4  530.94
   206.1     531   214.7  528.94     222  527.66   229.7  528.37   237.8  529.16
   249.8  531.81   269.6  531.42   281.5  531.86   293.4  533.71   305.2  534.86
     337  537.21   360.8  538.35   380.6   540.1   388.4   540.1   396.2  540.89
     404  542.98   431.4  552.45   439.2   554.8   462.6  563.44   482.2     570
#Mann= 3 ,-1 , 0
       0     .12       0   214.7    .045       0   229.7     .12       0
#XS Ineff= 2 , 0
                          266.25          532.92
Permanent Ineff=
       F       F
Bank Sta=214.7,229.7
XS Rating Curve= 0 ,0
Exp/Cntr=0.3,0.1

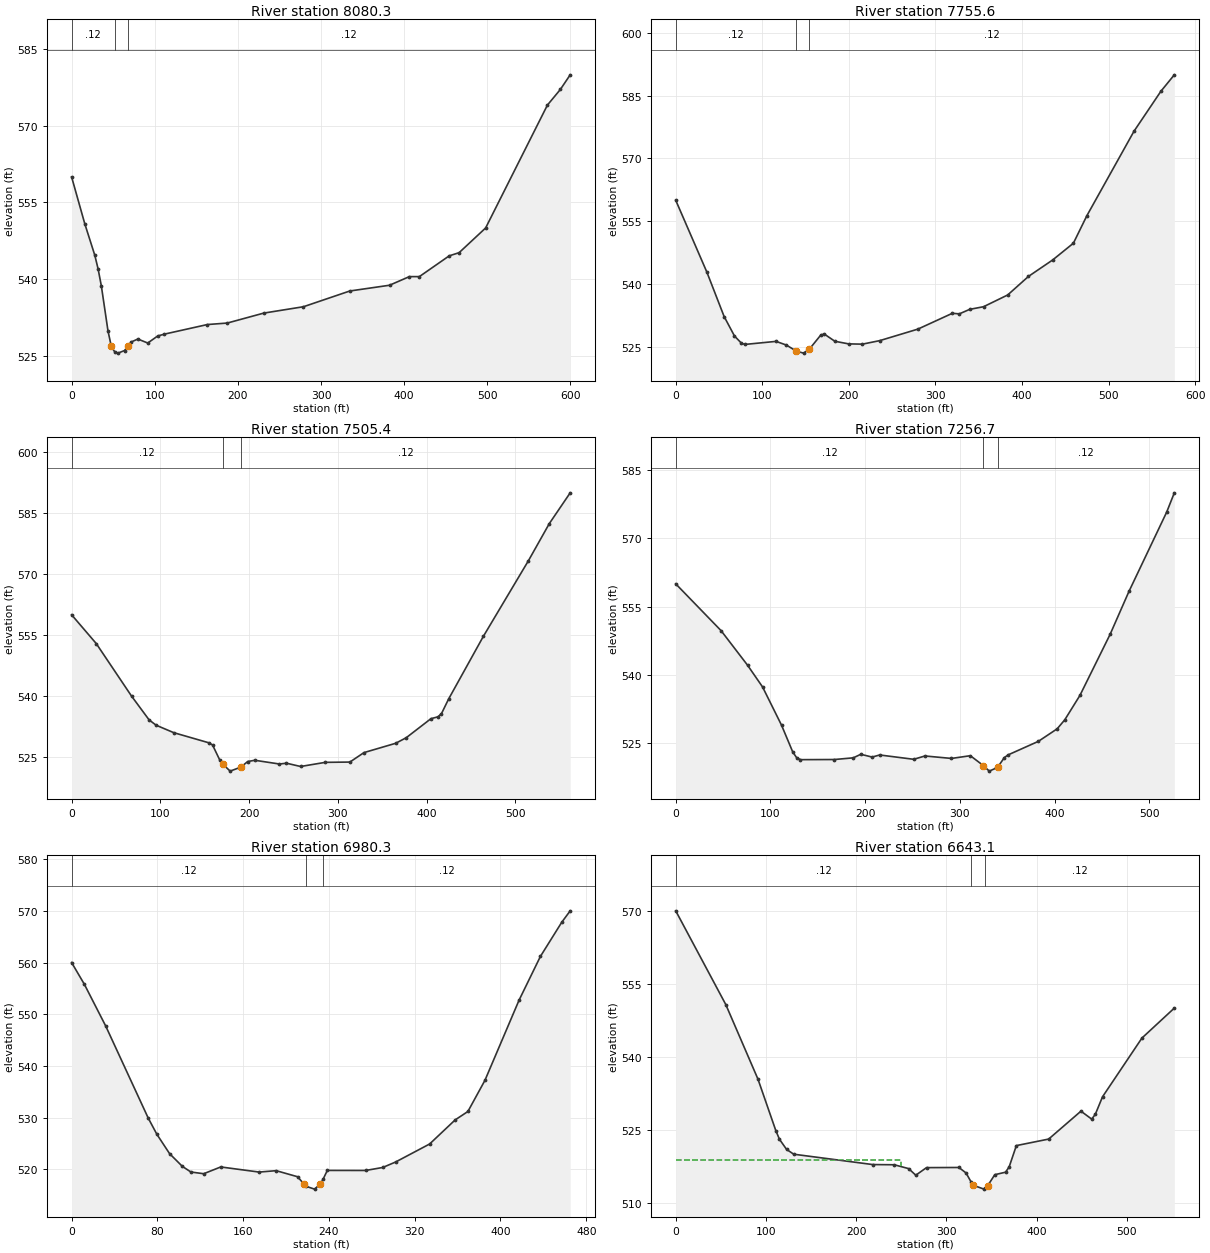
Type RM Length L Ch R = 1 ,8080.3  ,327.3,324.6,321.2
XS GIS Cut Line= 3
     2348547.206      422781.446     2348780.114        422341.3
     2348757.687       422242.11
#Sta/Elev= 30
       0     560    15.9   550.8    27.9  544.66    31.9  541.96    35.8  538.63
    43.8  529.81    47.8  526.78    51.8  525.75    55.8  525.48    63.7  525.99
    67.7  526.84    71.7  527.66    79.7  528.24    91.6  527.46   103.6  528.84
   111.6   529.2   163.3  531.08   187.2  531.37   231.1  533.32   278.9  534.57
   334.6  537.65   382.4  538.78   406.3  540.47   418.3  540.47   454.2  544.54
   466.1  545.16     498     550   572.3  574.07   587.9  577.14   599.7     580
#Mann= 3 ,-1 , 0
       0     .12       0    51.8    .045       0    67.7     .12       0
Bank Sta=47.8,67.7
XS Rating Curve= 0 ,0
Exp/Cntr=0.3,0.1

Type RM Length L Ch R = 1 ,7755.6  ,258.1,250.2,242.2
XS GIS Cut Line= 3
     2348802.854      422957.798     2348937.856      422518.627
     2349026.645      422443.068
#Sta/Elev= 30
       0     560      36   542.8    55.9  532.19    67.9  527.52    75.9  525.81
    79.9  525.51   115.9  526.24   127.8  525.36   139.5  523.89   147.8  523.43
   154.5  524.41   167.8  527.81   171.8  527.97   183.8  526.27   199.8  525.64
   215.7  525.58   235.7  526.42   279.7  529.17   319.6  532.96   327.6  532.82
   339.6   533.9   355.6  534.53   383.5  537.34   407.5  541.78   435.5  545.72
   459.4  549.72     475  556.31   529.4   576.5   560.5  586.07     576     590
#Mann= 3 ,-1 , 0
       0     .12       0   139.5    .045       0   154.5     .12       0
Bank Sta=139.5,154.5
XS Rating Curve= 0 ,0
Exp/Cntr=0.3,0.1

Type RM Length L Ch R = 1 ,7505.4  ,244.3,248.7,252.1
XS GIS Cut Line= 3
     2349069.347       423069.77     2349059.545       422645.22
     2349088.114      422511.213
#Sta/Elev= 30
       0     560    27.8  552.91    67.5     540    87.3  534.14    95.2  532.83
   115.1  530.99   154.8  528.49   158.8  527.96   166.7  524.36   170.7  523.19
   178.6  521.53   190.5   522.5   198.4  523.89   206.4   524.2   234.2  523.28
   242.1  523.48     258  522.67   285.8  523.69   313.5  523.76   329.4  526.09
   365.1  528.38     377  529.75   404.8  534.43   412.8   534.9   416.7  535.68
   424.7  539.26   463.8  554.66   514.7  573.32   538.2  582.44   561.7     590
#Mann= 3 ,-1 , 0
       0     .12       0   170.7    .045       0   190.5     .12       0
Bank Sta=170.7,190.5
XS Rating Curve= 0 ,0
Exp/Cntr=0.3,0.1

Type RM Length L Ch R = 1 ,7256.7  ,270.2,276.4,282.2
XS GIS Cut Line= 2
     2349190.669      423122.697     2349303.991      422608.537
#Sta/Elev= 30
       0     560    47.9  549.71    75.8  542.13    91.7  537.34   111.7  528.95
   123.6  523.04   127.6  521.82   131.6  521.36   167.5  521.39   187.5  521.76
   195.4  522.54   207.4  521.93   215.4  522.39   251.3  521.44   263.2  522.17
   291.2  521.63   311.1  522.23   324.8  520.07   331.1  518.84   339.8  519.65
     347  521.81     351  522.41   382.9  525.38   402.8  528.14   410.8  530.11
   426.8  535.47   458.7   548.9   478.6  558.33   518.5  575.79   526.5     580
#Mann= 3 ,-1 , 0
       0     .12       0   324.8    .045       0   339.8     .12       0
Bank Sta=324.8,339.8
XS Rating Curve= 0 ,0
Exp/Cntr=0.3,0.1

Type RM Length L Ch R = 1 ,6980.3  ,342.1,337.3,329
XS GIS Cut Line= 2
     2349347.531      423140.537     2349560.114      422726.941
#Sta/Elev= 30
       0     560    11.9  555.79    31.8  547.72    71.5  529.89    79.5  526.78
    91.4  523.02   103.3  520.56   111.3  519.47   123.2  519.14   139.1  520.45
   174.9  519.46   190.8  519.73   210.7  518.56  216.76 517.147   218.6  516.71
   226.6  516.16  232.09517.1863   234.5  518.06   238.5  519.78   274.2  519.77
   290.2  520.35   302.1   521.4   333.9  524.89   357.7  529.55   369.6  531.18
   385.5  537.21   417.3  552.71   437.2  561.17   457.1  567.78     465     570
#Mann= 3 ,-1 , 0
       0     .12       0   218.6    .045       0   234.5     .12       0
Bank Sta=216.76,232.09
XS Rating Curve= 0 ,0
Exp/Cntr=0.3,0.1

Type RM Length L Ch R = 1 ,6643.1  ,331.8,325.5,319.1
XS GIS Cut Line= 3
     2349550.285      423308.537     2349676.114       423260.25
     2349716.114       422844.28
#Sta/Elev= 30
       0     570    55.5  550.73    91.2  535.38     111  524.79     115  523.03
   122.9  520.95   130.8  519.96   218.4  517.83   242.2  517.79   258.2     517
   266.1  515.64     278   517.2   313.9  517.23   321.8  516.11   327.5  514.23
   329.8  513.58   341.7  512.78   342.5  512.91   345.7  513.45   353.7  515.75
   365.6  516.26   369.6  517.34   377.6  521.73   413.4  523.07   449.2  528.81
   461.1  527.18   465.1  528.15   473.1  531.76   516.8  543.84   552.7     550
#Mann= 3 ,-1 , 0
       0     .12       0   327.5    .045       0   342.5     .12       0
#XS Ineff= 2 , 0
          249.29  518.85
Permanent Ineff=
       F       F
Bank Sta=329.8,345.7
XS Rating Curve= 0 ,0
Exp/Cntr=0.3,0.1

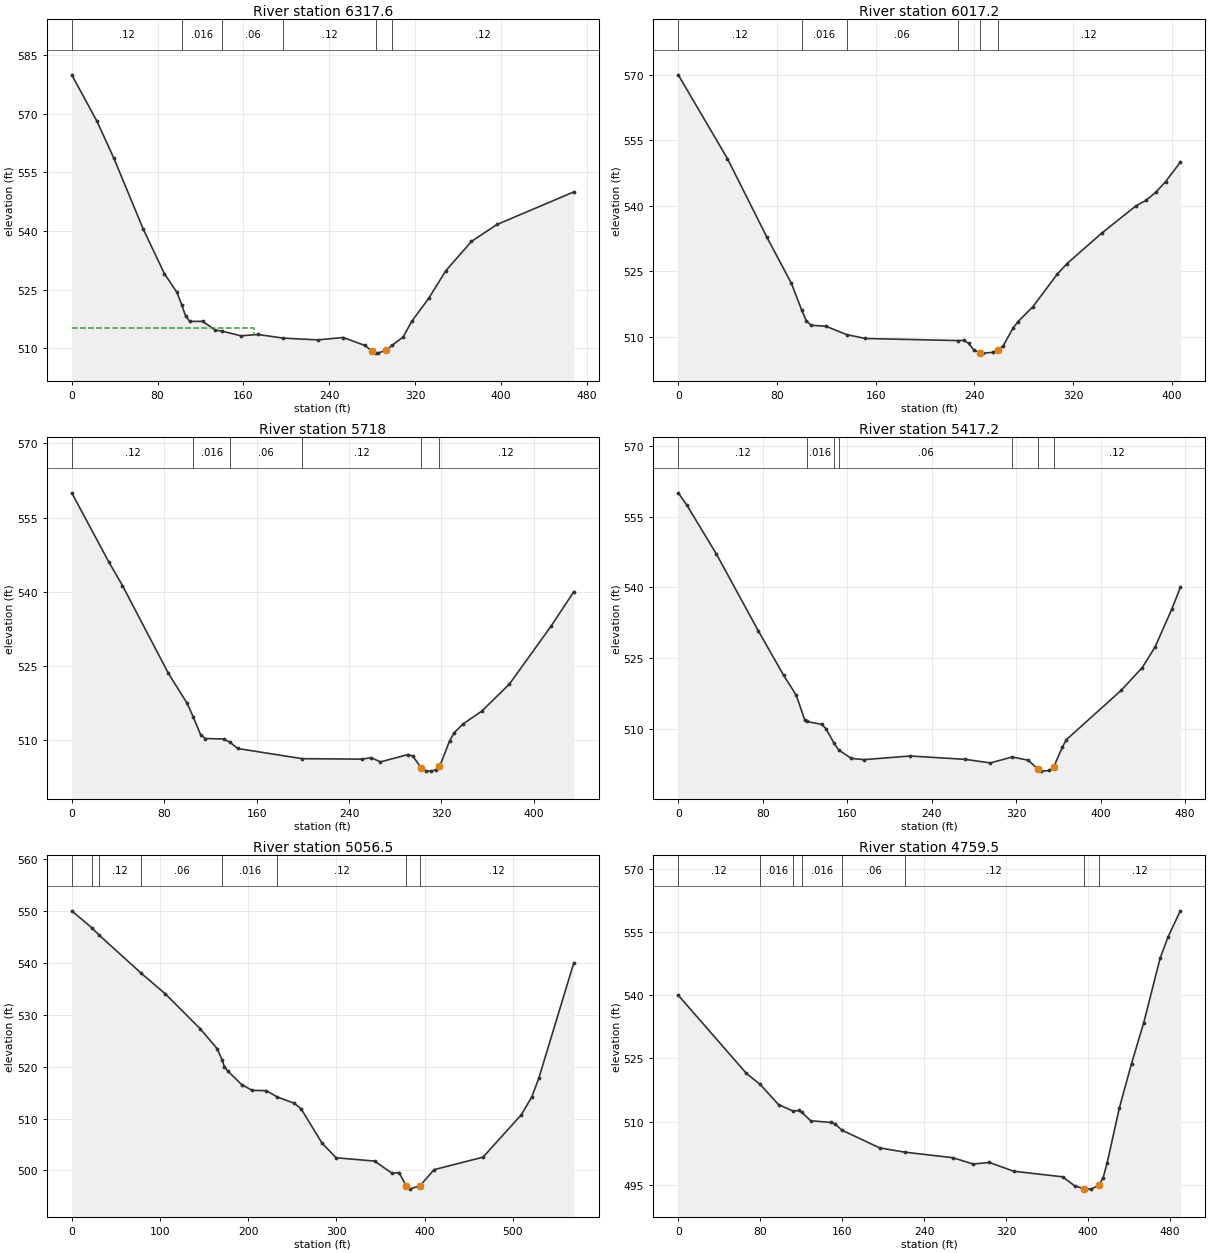
Type RM Length L Ch R = 1 ,6317.6  ,305.2,300.3,295.3
XS GIS Cut Line= 3
     2350089.322      423317.745     2350052.044       423222.83
     2349985.406      422862.982
#Sta/Elev= 30
       0  579.98    23.5  568.08    39.2  558.64    66.7  540.43    86.3  529.08
      98  524.29  102.54521.0334     106   518.3   109.9  516.84   121.9  516.86
   133.8  514.62  140.11514.3496   157.7  513.16   173.6  513.49   197.2512.5621
   229.3  512.11   253.1  512.72     273   510.7  279.69509.2802   283.5  508.81
     285  508.72   292.9  509.42   298.5 510.712   308.8  512.85   316.8  516.84
   332.7  522.77   348.6  529.82   372.5  537.33   396.3  541.66   467.9     550
#Mann= 6 ,-1 , 0
       0     .12       0  102.54    .016       0  140.11     .06       0
   197.2     .12       0   283.5    .045       0   298.5     .12       0
#XS Ineff= 2 , 0
          169.59   515.2
Permanent Ineff=
       F       F
Bank Sta=279.69,292.9
XS Rating Curve= 0 ,0
Exp/Cntr=0.3,0.1

Type RM Length L Ch R = 1 ,6017.2  ,296.5,299.3,302
XS GIS Cut Line= 2
     2350401.285       423177.62     2350241.703      422803.428
#Sta/Elev= 30
       0     570    39.9  550.81    71.8  532.86    91.7  522.28  100.02516.1704
   103.7  513.76   107.7  512.68   119.6  512.47   136.5 510.548   151.6  509.66
  226.32509.1873   231.3  509.23   235.3  508.55   239.3  507.08   244.3   506.4
   247.3  506.31   255.2  506.49   259.3  507.11   263.2  507.94   271.2  512.02
   275.2  513.49   287.2  516.88   307.1  524.39   315.1  526.82     343  533.74
   370.9  540.02   378.9  541.26   386.9  543.12   394.8  545.54   406.8     550
#Mann= 6 ,-1 , 0
       0     .12       0  100.02    .016       0   136.5     .06       0
  226.32     .12       0   244.3    .045       0   259.3     .12       0
Bank Sta=244.3,259.3
XS Rating Curve= 0 ,0
Exp/Cntr=0.3,0.1

Type RM Length L Ch R = 1 ,5718    ,296.1,300.7,305.3
XS GIS Cut Line= 2
      2350667.71      423137.707     2350547.623      422719.993
#Sta/Elev= 30
       0     560    31.9  546.08    43.9  541.23    83.7  523.44    99.7  517.47
  105.11514.6758   111.6  511.02   115.6  510.28   131.6  510.18   137.3509.4787
   143.6  508.26  199.48 506.199   251.2  506.11   259.2   506.4   267.2  505.55
   291.1  507.04   295.1  506.75   302.7  504.27     307   503.7     311  503.68
     315  503.93   317.7  504.63     319  504.96     327  509.77     331  511.46
   338.9  513.26   354.9  515.82   378.8  521.29   414.7  532.96   434.6     540
#Mann= 6 ,-1 , 0
       0     .12       0  105.11    .016       0   137.3     .06       0
  199.48     .12       0   302.7    .045       0   317.7     .12       0
Bank Sta=302.7,317.7
XS Rating Curve= 0 ,0
Exp/Cntr=0.3,0.1

Type RM Length L Ch R = 1 ,5417.2  ,356.2,360.8,365.3
XS GIS Cut Line= 2
     2350904.793      423141.279      2350868.73      422667.295
#Sta/Elev= 30
       0  560.01       8  557.47      36  547.12    75.9  530.79    99.9  521.39
   111.8  517.18   119.8  511.95  121.51511.6636   135.8  511.04   139.8  510.15
  147.69507.0054  151.96505.6184   163.8  503.85   175.8  503.58   219.7  504.35
   271.6  503.64   295.6  502.88  316.08504.1484   331.6  503.45   340.4  501.58
   343.5  501.15   351.5  501.29   355.4  501.94   363.5  506.15   367.5   507.8
   419.4  518.23   439.4  523.06   451.4  527.37   467.4  535.43   475.4     540
#Mann= 7 ,-1 , 0
       0     .12       0  121.51    .016       0  147.69     .12       0
  151.96     .06       0  316.08     .12       0   340.4    .045       0
   355.4     .12       0
Bank Sta=340.4,355.4
XS Rating Curve= 0 ,0
Exp/Cntr=0.3,0.1

Type RM Length L Ch R = 1 ,5056.5  ,294.8,297,299.3
XS GIS Cut Line= 3
      2351052.81      423163.842      2351195.06      423065.591
     2351244.072      422672.495
#Sta/Elev= 30
       0  549.99   22.97546.6887   31.14 545.294   78.83537.9557   106.1  533.99
   145.4   527.3     165  523.41  170.15521.3568   172.9  520.01   176.8  519.16
   192.7   516.5   204.6  515.41   220.4  515.37  232.96 514.139   252.1  512.94
     260  511.84   283.8  505.22   299.6  502.44   343.2   501.8     363  499.45
     371  499.59   378.9  497.04   382.8   496.4   394.7  497.06   410.6  500.15
     466  502.55   509.6  510.74   521.5  514.22   529.4  517.82     569     540
#Mann= 8 ,-1 , 0
       0     .12       0   22.97     .06       0   31.14     .12       0
   78.83     .06       0  170.15    .016       0  232.96     .12       0
   378.9    .045       0   394.7     .12       0
Bank Sta=378.9,394.7
XS Rating Curve= 0 ,0
Exp/Cntr=0.3,0.1

Type RM Length L Ch R = 1 ,4759.5  ,311.8,307.5,303.2
XS GIS Cut Line= 3
     2351481.314      423229.738     2351454.793      423095.188
     2351533.543      422751.108
#Sta/Elev= 30
       0     540    66.6  521.45   80.06518.8367      98  514.04  112.46512.5029
   117.6  512.69  120.72 512.226   129.3  510.24     149  509.84     153  509.54
  159.71508.0173   196.6  503.82  221.31502.7945     268  501.49   287.8  499.99
   303.7  500.36   327.5  498.28   375.1  496.96     387  494.82   395.6  494.17
   402.9  494.04   410.6  494.92   414.8  496.77   418.7  500.28   430.6  513.29
   442.5  523.81   454.4  533.48   470.3   548.7   478.2  553.85   490.1  559.99
#Mann= 8 ,-1 , 0
       0     .12       0   80.06    .016       0  112.46     .12       0
  120.72    .016       0  159.71     .06       0  221.31     .12       0
   395.6    .045       0   410.6     .12       0
Bank Sta=395.6,410.6
XS Rating Curve= 0 ,0
Exp/Cntr=0.3,0.1