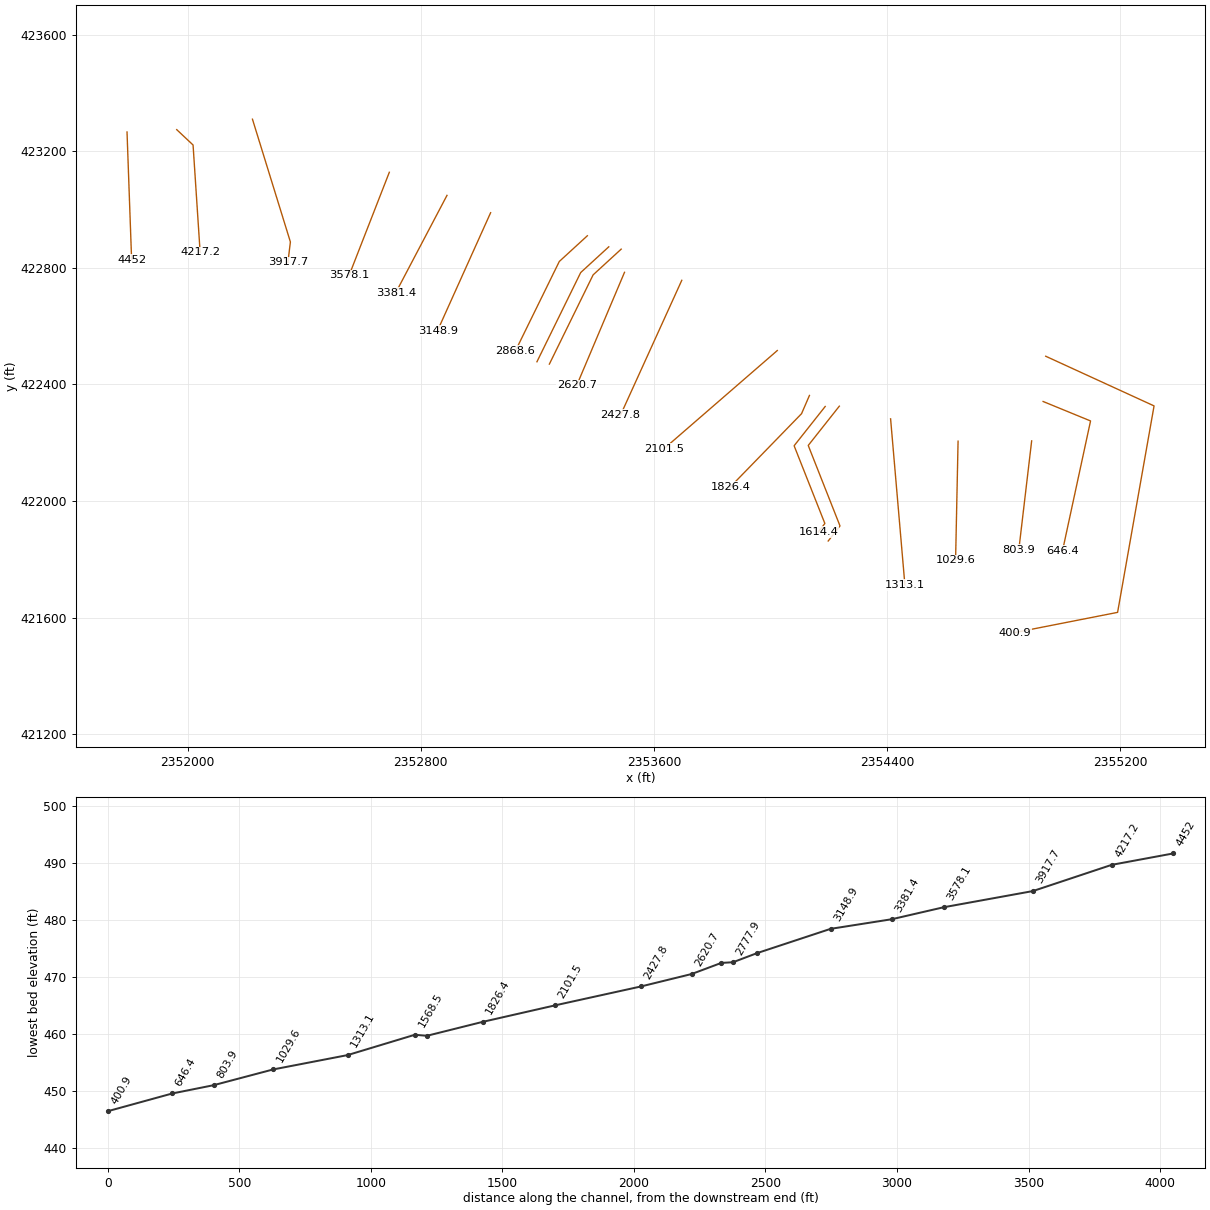
HEC-RAS study SWIMRUN.prj: SWIMRUN

--- SWIMRUN.g01 (geometry) --- (continued)

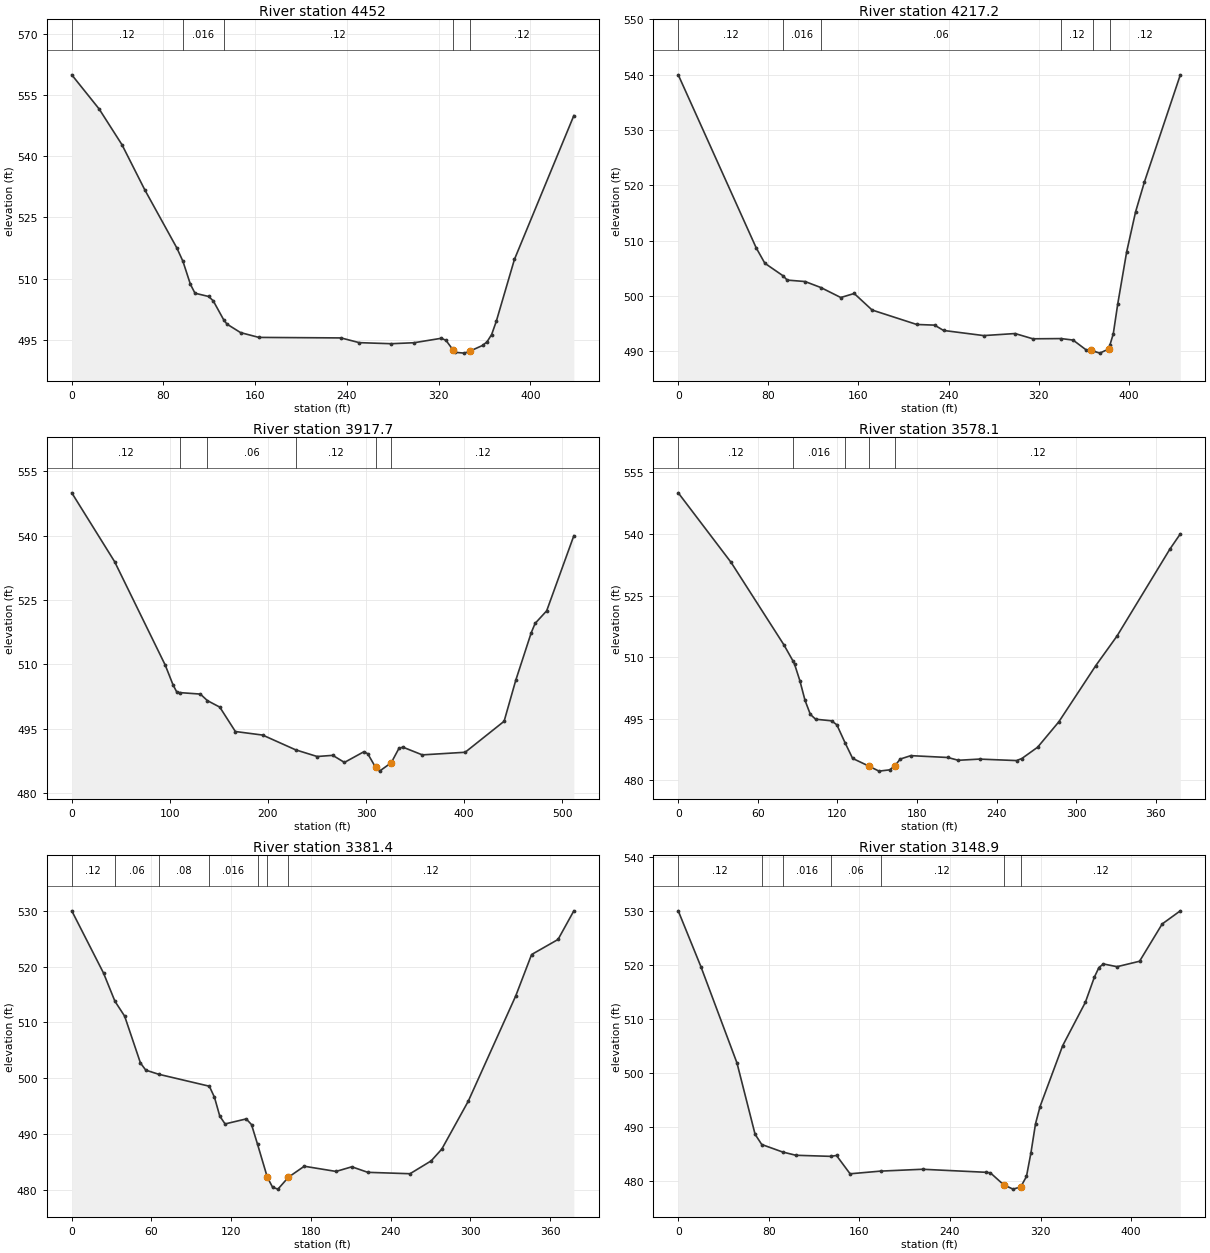
Type RM Length L Ch R = 1 ,4452    ,234,234.7,235.4
XS GIS Cut Line= 2
     2351792.114      423265.975     2351807.842      422828.264
#Sta/Elev= 30
       0     560    23.9  551.61    43.8  542.85    63.7  531.78    91.6  517.55
   96.94514.2742   103.5   508.6   107.5  506.41   119.4  505.61   123.4  504.55
  132.55499.8773   135.4  498.83   147.3  496.74   163.2  495.57   234.9  495.44
   250.8  494.28   278.7  494.02   298.6  494.26   322.5  495.36   326.5  494.83
   332.4  492.57   334.5  491.91   342.4  491.71   347.4  492.21   358.4   493.6
   362.3   494.5   366.3  496.28   370.3  499.48   386.2  514.73     438     550
#Mann= 5 ,-1 , 0
       0     .12       0   96.94    .016       0  132.55     .12       0
   332.4    .045       0   347.4     .12       0
Bank Sta=332.4,347.4
XS Rating Curve= 0 ,0
Exp/Cntr=0.3,0.1

Type RM Length L Ch R = 1 ,4217.2  ,294.3,299.5,304.7
XS GIS Cut Line= 3
     2351962.678      423273.974     2352018.742      423221.318
     2352042.949      422853.372
#Sta/Elev= 30
       0     540    69.2  508.73    76.9  505.94   93.18503.6581    96.7   502.9
   112.6  502.64  126.54501.5611   144.3  499.75   156.2  500.48   172.1  497.49
   211.7  494.88   227.6  494.76   235.5   493.8   271.2  492.87     299  493.24
   314.8  492.29  339.93  492.33   350.5  492.06   362.4  490.24   366.4  490.27
   368.3  490.08   374.3   489.7   382.2  490.47   383.3  491.22   386.2  493.19
   390.2  498.64   398.1  508.03     406  515.24   413.9  520.68   445.7  539.99
#Mann= 6 ,-1 , 0
       0     .12       0   93.18    .016       0  126.54     .06       0
  339.93     .12       0   368.3    .045       0   383.3     .12       0
Bank Sta=366.4,382.2
XS Rating Curve= 0 ,0
Exp/Cntr=0.3,0.1

Type RM Length L Ch R = 1 ,3917.7  ,355,339.6,324.3
XS GIS Cut Line= 3
     2352222.515      423309.856     2352352.674       422888.67
     2352344.114      422818.152
#Sta/Elev= 30
       0     550    43.7  533.94    95.3  509.82   103.3  505.18   107.2  503.48
   110.5503.3975   131.1  503.06  138.29501.5357   150.9  500.02   166.8  494.33
   194.6   493.5  228.23 490.059   250.2   488.5   266.1  488.77     278  487.12
   297.9  489.62   301.8  489.13   309.8  485.96   313.8  485.09   325.7  487.04
   333.6  490.41   337.6  490.68   357.4  488.88   401.1  489.49   440.8  496.72
   452.7   506.3   468.5   517.4   472.4  519.54   484.2  522.48   511.9     540
#Mann= 6 ,-1 , 0
       0     .12       0   110.5    .016       0  138.29     .06       0
  228.23     .12       0   309.8    .045       0   325.7     .12       0
Bank Sta=309.8,325.7
XS Rating Curve= 0 ,0
Exp/Cntr=0.3,0.1

Type RM Length L Ch R = 1 ,3578.1  ,199.2,196.7,194.2
XS GIS Cut Line= 2
     2352692.114      423127.685     2352554.516      422774.939
#Sta/Elev= 30
       0     550    39.9  533.04    79.7  512.98   86.35509.1641    87.7  508.29
    91.7  504.28    95.6  499.48    99.6  496.07   103.6  494.88   115.6  494.49
   119.6  493.52  125.81489.1396   131.5  485.34   143.5   483.5   151.4  482.24
   159.4  482.55   163.4  483.56   167.4  485.18   175.4  486.01   203.3  485.56
   211.2  484.88   227.2  485.17   255.1  484.81   259.1  485.31     271  488.06
     287  494.25   314.9  507.95   330.8   515.1   370.7  536.28   378.6     540
#Mann= 5 ,-1 , 0
       0     .12       0   86.35    .016       0  125.81     .12       0
   143.5    .045       0   163.4     .12       0
Bank Sta=143.5,163.4
XS Rating Curve= 0 ,0
Exp/Cntr=0.3,0.1

Type RM Length L Ch R = 1 ,3381.4  ,232.1,232.5,232.8
XS GIS Cut Line= 2
     2352890.024      423048.537     2352714.025      422714.085
#Sta/Elev= 30
       0     530    23.9  518.85    32.5513.7943    39.8  511.13    51.7  502.74
    55.7  501.46   65.42500.7199  103.54498.5782   107.4   496.6   111.4  493.22
   115.4  491.82   131.3  492.72   135.3   491.7  139.83488.1751   147.2  482.26
   151.2  480.46   155.2  480.14   163.1  482.28     175  484.24   198.9  483.31
   210.8  484.14   222.8  483.15   254.6   482.9   270.5   485.2   278.5  487.31
   298.4  495.88   334.2  514.78   346.1  522.17     366  524.87   377.9     530
#Mann= 7 ,-1 , 0
       0     .12       0    32.5     .06       0   65.42     .08       0
  103.54    .016       0  139.83     .12       0   147.2    .045       0
   163.1     .12       0
Bank Sta=147.2,163.1
XS Rating Curve= 0 ,0
Exp/Cntr=0.3,0.1

Type RM Length L Ch R = 1 ,3148.9  ,281.1,280.3,279.6
XS GIS Cut Line= 2
     2353039.693      422988.958     2352857.693      422584.537
#Sta/Elev= 30
       0     530      20  519.67    51.9  501.81    67.9   488.6   73.77486.7155
    92.1485.3335   103.9  484.72  134.52484.5216   139.8  484.68   151.8  481.29
  178.72481.7865   215.8  482.13   271.7  481.57   275.7  481.47   287.5  479.25
   295.7  478.45   302.5  478.85   307.6  480.79   311.6  485.23   315.6  490.56
   319.6  493.75   339.6  505.03   359.6  513.04   367.6  517.72   371.6   519.5
   375.6  520.16   387.6  519.65   407.5  520.66   427.5  527.57   443.5     530
#Mann= 7 ,-1 , 0
       0     .12       0   73.77     .08       0    92.1    .016       0
  134.52     .06       0  178.72     .12       0   287.5    .045       0
   302.5     .12       0
Bank Sta=287.5,302.5
XS Rating Curve= 0 ,0
Exp/Cntr=0.3,0.1

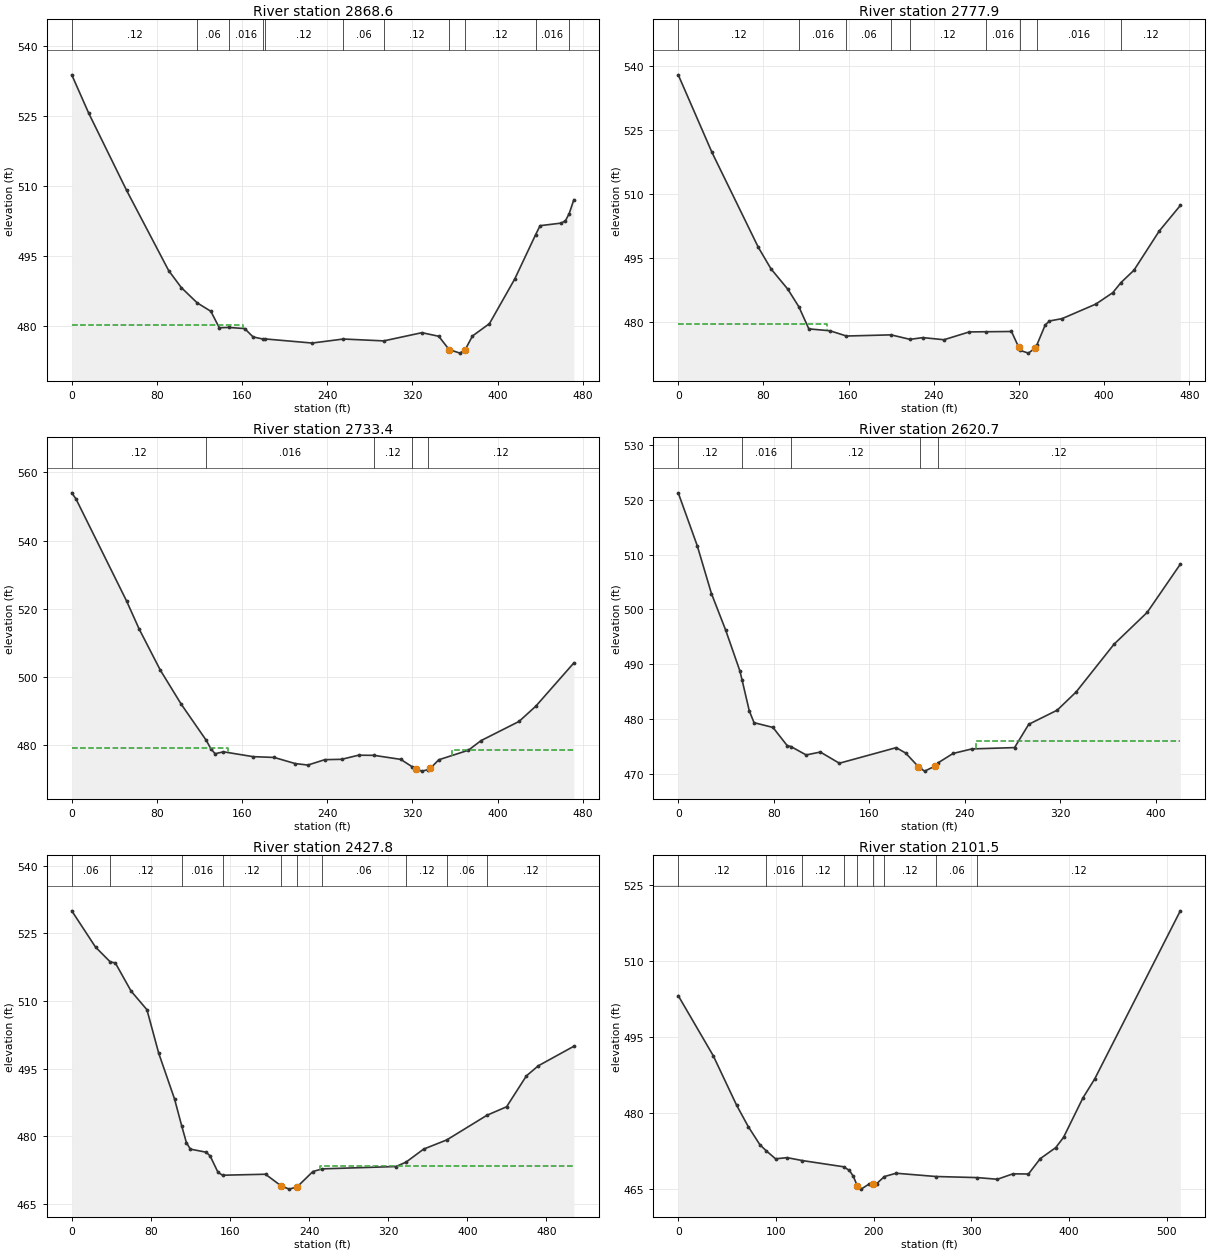
Type RM Length L Ch R = 1 ,2868.6  ,90.4,90.7,90.9
XS GIS Cut Line= 3
     2353371.594      422909.856     2353275.305      422821.584
     2353125.168      422515.446
#Sta/Elev= 30
       0  533.78    15.8  525.62    51.5  509.03      91  491.86   102.9  488.21
  117.81484.9382   130.6  483.14   138.6   479.6  147.22479.6756   162.4  479.43
   170.3  477.64  179.61477.1841  181.83477.2063   225.8  476.33  255.05 477.191
  293.04476.7908   328.9  478.55   344.7  477.78   354.4  474.94   364.6  474.17
   369.4  474.86   376.4  477.85   392.3  480.48   416.1  490.06  435.64  499.52
   439.9  501.47   459.7  502.02   463.7  502.52  467.22504.0544   471.6  507.03
#Mann= 11 ,-1 , 0
       0     .12       0  117.81     .06       0  147.22    .016       0
  179.61     .06       0  181.83     .12       0  255.05     .06       0
  293.04     .12       0   354.4    .045       0   369.4     .12       0
  435.64    .016       0  467.22     .12       0
#XS Ineff= 2 , 0
          160.47  480.29
Permanent Ineff=
       F       F
Bank Sta=354.4,369.4
XS Rating Curve= 0 ,0
Exp/Cntr=0.3,0.1

Type RM Length L Ch R = 1 ,2777.9  ,44.5,44.5,44.5
XS GIS Cut Line= 3
     2353445.074       422871.93     2353348.785      422783.658
     2353198.648      422477.521
#Sta/Elev= 30
       0  538.04    31.7  519.79    75.2  497.48    87.1  492.41   102.9  487.63
  113.31483.4799   122.7  478.28   142.5  477.84  158.01476.6034   199.9476.8767
  217.69475.8211   229.8  476.23   249.6  475.73   273.4  477.57  289.15  477.61
     313  477.67  319.81 473.985   320.9  473.25   328.9  472.58  334.86473.6888
   336.8  474.46   344.7   479.2   348.7  480.14   360.6   480.7   392.3  484.12
   408.2  486.81  415.87489.1776     428  492.06   451.8   501.3   471.6  507.31
#Mann= 9 ,-1 , 0
       0     .12       0  113.31    .016       0  158.01     .06       0
   199.9    .016       0  217.69     .12       0  289.15    .016       0
   320.9    .045       0   336.8    .016       0  415.87     .12       0
#XS Ineff= 2 , 0
          139.32  479.34
Permanent Ineff=
       F       F
Bank Sta=319.81,334.86
XS Rating Curve= 0 ,0
Exp/Cntr=0.3,0.1

Type RM Length L Ch R = 1 ,2733.4  ,111.4,112.6,113.9
XS GIS Cut Line= 3
      2353487.74      422864.029     2353391.451      422775.757
     2353241.314       422469.62
#Sta/Elev= 30
       0  553.97       4  552.16    51.5  522.28    63.3  514.08    83.1  502.08
   102.9  492.02  126.35481.4627   130.6  479.05   134.6  477.55   142.5  478.12
   170.3   476.7   190.1  476.47   209.9  474.67   221.8  474.24   237.7  475.82
   253.5  475.92   269.4  477.13  283.94477.0808     309   475.9   319.5  473.79
     323473.0468   328.9  472.46   334.5  472.88   336.8  473.27   344.7  475.78
   372.5  478.58   384.4  481.39   420.1  487.01   435.9  491.49   471.6  504.15
#Mann= 5 ,-1 , 0
       0     .12       0  126.35    .016       0  283.94     .12       0
   319.5    .045       0   334.5     .12       0
#XS Ineff= 2 , 0
          146.54  479.26  357.07          478.75
Permanent Ineff=
       F       F
Bank Sta=323,336.8
XS Rating Curve= 0 ,0
Exp/Cntr=0.3,0.1

Type RM Length L Ch R = 1 ,2620.7  ,193.3,192.9,192.6
XS GIS Cut Line= 2
     2353499.078      422784.411     2353335.417       422397.12
#Sta/Elev= 30
       0  521.25    15.9  511.62    27.8  502.89    39.7  496.23    51.6  488.79
    53.5487.0849    59.5  481.49    63.5  479.34    79.3  478.48    91.2  475.17
    94.3474.9995   107.1  473.46     119  473.99   134.9  471.95   182.5  474.79
   190.4  473.81  201.09 471.322   202.7  471.02   206.3  470.51  214.98471.4183
   217.7  472.04   230.1  473.73   245.9  474.56   281.6   474.8   293.5  479.05
   317.3  481.62   333.2  484.95   364.9  493.65   392.7  499.46   420.4  508.24
#Mann= 5 ,-1 , 0
       0     .12       0    53.5    .016       0    94.3     .12       0
   202.7    .045       0   217.7     .12       0
#XS Ineff= 2 , 0
                          249.23          475.98
Permanent Ineff=
       F       F
Bank Sta=201.09,214.98
XS Rating Curve= 0 ,0
Exp/Cntr=0.3,0.1

Type RM Length L Ch R = 1 ,2427.8  ,336.2,326.3,316.3
XS GIS Cut Line= 2
      2353695.61      422757.041     2353485.588      422294.842
#Sta/Elev= 30
       0  529.99      24  521.96   38.98518.6557      44  518.46      60   512.2
      76  508.08    87.9  498.45   103.9  488.31  111.07482.4121   115.9  478.64
   119.9  477.19   135.9   476.5   139.9  475.68   147.9  472.03  152.51471.4014
   195.9  471.62   211.9  469.01   219.9  468.32   227.9  468.82   243.8  472.22
  253.43472.8115   327.8  473.33  338.03474.3024   355.8  477.19   379.2 479.225
   419.9484.6955   439.7  486.57   459.7  493.41   471.7  495.64   507.7  499.98
#Mann= 10 ,-1 , 0
       0     .06       0   38.98     .12       0  111.07    .016       0
  152.51     .12       0   211.9    .045       0   227.9     .12       0
  253.43     .06       0  338.03     .12       0   379.2     .06       0
   419.9     .12       0
#XS Ineff= 2 , 0
                          251.06          473.54
Permanent Ineff=
       F       F
Bank Sta=211.9,227.9
XS Rating Curve= 0 ,0
Exp/Cntr=0.3,0.1

Type RM Length L Ch R = 1 ,2101.5  ,272.8,275,277.2
XS GIS Cut Line= 2
     2354023.357      422516.056     2353635.132      422179.555
#Sta/Elev= 30
       0  503.23    35.8  491.37    59.7   481.6    71.7  477.34    83.6  473.77
   89.89472.6037    99.6  470.99   111.5  471.22   126.8470.6508  169.24469.4157
   175.2  468.69   179.2  467.52   183.2  465.67   187.2     465   195.2     466
   199.1  465.99   203.1  466.08  210.93467.4851     223  468.14  263.77467.4927
  306.22467.2776   326.6  466.95   342.5  468.02   358.4  467.99   370.4  471.01
   386.3   473.2   394.3  475.23   414.2  483.05   426.1  486.74   513.8  519.99
#Mann= 9 ,-1 , 0
       0     .12       0   89.89    .016       0   126.8     .12       0
  169.24     .06       0   183.2    .045       0   199.1     .06       0
  210.93     .12       0  263.77     .06       0  306.22     .12       0
Bank Sta=183.2,199.1
XS Rating Curve= 0 ,0
Exp/Cntr=0.3,0.1

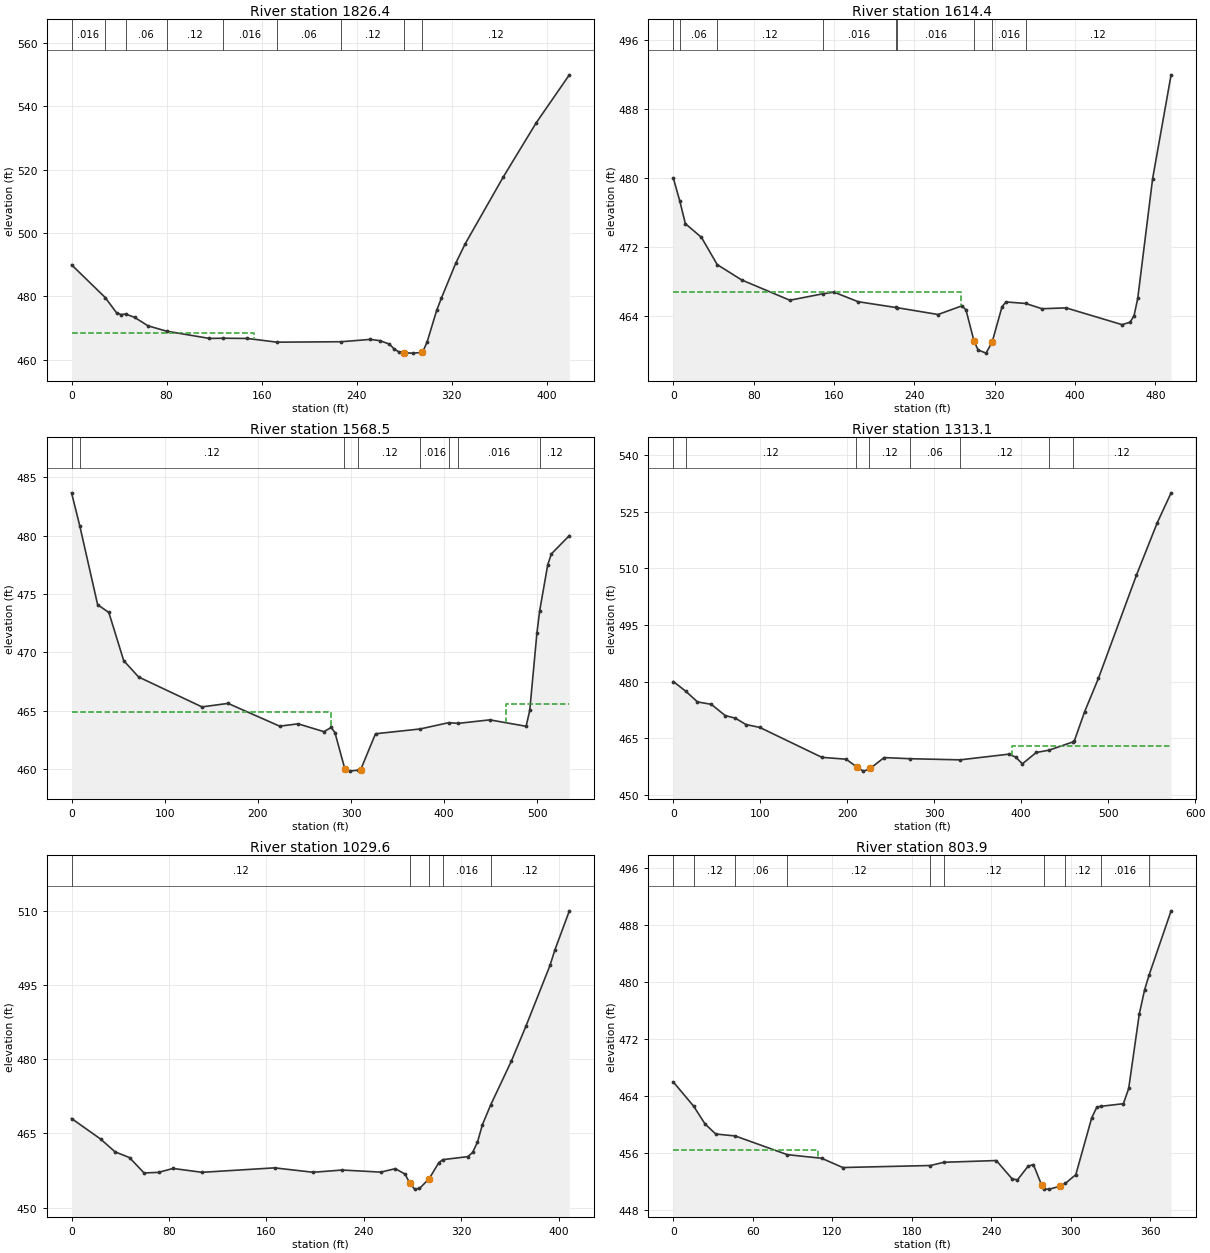
Type RM Length L Ch R = 1 ,1826.4  ,185.4,212,238.3
XS GIS Cut Line= 3
     2354133.643      422361.977     2354106.578      422299.421
     2353861.997      422048.004
#Sta/Elev= 30
       0     490   28.35479.6557    37.9  474.82    41.6  474.27   45.53474.4591
      53   473.4    64.4  470.72   79.97 469.032     116  466.74   127.2 466.808
   147.9  466.74  172.84  465.56  226.86   465.7   251.5  466.44   259.5  466.03
   267.4  464.97   271.4  463.45   275.4  462.48   279.7  462.18   287.4   462.1
   294.7   462.3   295.4  462.34   299.3  465.74   307.3  475.65   311.3  479.54
   323.3   490.5   331.2   496.6   363.1  517.61     391  534.84   418.9     550
#Mann= 9 ,-1 , 0
       0    .016       0   28.35     .12       0   45.53     .06       0
   79.97     .12       0   127.2    .016       0  172.84     .06       0
  226.86     .12       0   279.7    .045       0   294.7     .12       0
#XS Ineff= 2 , 0
          153.19  468.38
Permanent Ineff=
       F       F
Bank Sta=279.7,294.7
XS Rating Curve= 0 ,0
Exp/Cntr=0.3,0.1

Type RM Length L Ch R = 1 ,1614.4  ,46,45.9,45.9
XS GIS Cut Line= 4
     2354187.768       422324.19     2354081.065      422189.347
     2354186.546      421922.694     2354164.114      421893.433
#Sta/Elev= 30
       0  480.01    6.55477.2911      12   474.7      28  473.11   43.71469.9399
      68  468.16     116   465.8  148.81466.5466     160  466.74   183.9  465.63
  221.42464.9551  222.86464.9329   263.6  464.14   287.4  465.15   291.4  464.67
   299.4  461.05   303.4  460.02   311.4  459.65   317.5  460.96   327.3  465.06
   331.3   465.6  350.75465.4234   367.1  464.81     391  464.91   446.8  462.96
   454.7  463.24   458.7  463.99   462.4  466.03   477.2  479.93   495.6     492
#Mann= 9 ,-1 , 0
       0    .016       0    6.55     .06       0   43.71     .12       0
  148.81    .016       0  221.42     .06       0  222.86    .016       0
   299.4    .045       0   317.5    .016       0  350.75     .12       0
#XS Ineff= 2 , 0
          286.38  466.76
Permanent Ineff=
       F       F
Bank Sta=299.4,317.5
XS Rating Curve= 0 ,0
Exp/Cntr=0.3,0.1

Type RM Length L Ch R = 1 ,1568.5  ,262,255.4,248.9
XS GIS Cut Line= 4
     2354236.205      422325.232     2354129.503      422190.388
     2354238.454      421914.327     2354198.059      421862.592
#Sta/Elev= 30
       0  483.66    8.88 480.812      28  474.08      40  473.42      56  469.29
      72  467.89     140  465.33     168  465.63   223.4  463.68   243.2  463.88
   270.9  463.21   278.8  463.57   282.8  463.12     293  460.13  293.82459.9814
   298.6  459.83     308  459.92   310.4  459.96   326.3  463.03   374.4463.4423
  404.99463.9816  415.09463.9187     449  464.22     488  463.67   491.9  465.04
   499.6  471.66  502.46473.5153   511.2   477.5   515.1  478.43   534.4     480
#Mann= 8 ,-1 , 0
       0    .016       0    8.88     .12       0     293    .045       0
     308     .12       0   374.4    .016       0  404.99     .06       0
  415.09    .016       0  502.46     .12       0
#XS Ineff= 2 , 0
          278.64  464.88  466.25          465.59
Permanent Ineff=
       F       F
Bank Sta=293.82,310.4
XS Rating Curve= 0 ,0
Exp/Cntr=0.3,0.1

Type RM Length L Ch R = 1 ,1313.1  ,285.6,283.5,280.6
XS GIS Cut Line= 2
     2354412.114      422281.672     2354461.222       421711.43
#Sta/Elev= 30
       0     480   14.38477.4166    27.8   474.6    43.7  473.96    59.6  470.99
    71.5  470.28    83.5  468.61    99.4  467.84   170.9  459.91   198.7  459.42
   210.2   457.5   210.7  457.38   218.6  456.26   225.2  456.78   226.6     457
   242.4  459.85  272.12459.5487  329.86459.2495   385.5  460.75   393.5  460.02
   401.4  458.19   417.3   461.2  432.08461.8164  459.49463.9964   461.1  464.25
     473  472.02   488.9  480.89   532.6  508.22   556.4  522.03   572.4     530
#Mann= 8 ,-1 , 0
       0    .016       0   14.38     .12       0   210.2    .045       0
   225.2     .12       0  272.12     .06       0  329.86     .12       0
  432.08    .016       0  459.49     .12       0
#XS Ineff= 2 , 0
                          389.71             463
Permanent Ineff=
       F       F
Bank Sta=210.7,226.6
XS Rating Curve= 0 ,0
Exp/Cntr=0.3,0.1

Type RM Length L Ch R = 1 ,1029.6  ,227.6,225.6,223.2
XS GIS Cut Line= 2
      2354643.64      422205.011     2354635.073      421796.537
#Sta/Elev= 30
       0  468.01    23.8  463.86    35.7  461.27    47.6   460.1    59.5     457
    71.4  457.12    83.3  457.91   107.1  457.13   166.6  458.03   198.3  457.14
   222.1  457.59   253.9  457.17   265.8  457.87   273.7  456.77   277.7  454.92
   281.6  453.73   285.6  453.87   293.5  455.83   301.5   459.1  304.69459.6889
   325.3   460.3   329.2  461.15   333.2  463.24   337.2  466.73  343.97470.7281
     361  479.62   372.9  486.64   392.7  498.95   396.7  502.07   408.6     510
#Mann= 5 ,-1 , 0
       0     .12       0   277.7    .045       0   293.5     .12       0
  304.69    .016       0  343.97     .12       0
Bank Sta=277.7,293.5
XS Rating Curve= 0 ,0
Exp/Cntr=0.3,0.1

Type RM Length L Ch R = 1 ,803.9   ,159.6,157.5,155.5
XS GIS Cut Line= 2
     2354896.114      422206.046     2354852.114      421833.041
#Sta/Elev= 30
       0     466   15.39462.5908      24   460.1      32   458.7   46.74458.4274
   86.03455.8008   111.9   455.3   127.9     454  194.03454.2827  204.13454.7349
   243.7  454.98   255.7   452.4   259.7  452.27   267.7  454.19   271.7  454.42
  278.03451.4817   279.7  450.98   283.7  450.97   291.7  451.37   295.7  451.76
   303.7     453   315.7  460.97   319.6  462.48  322.56462.5836   339.6  462.95
   343.6  465.09   351.6  475.54   355.6  478.92  358.96 480.978   375.6     490
#Mann= 10 ,-1 , 0
       0     .06       0   15.39     .12       0   46.74     .06       0
   86.03     .12       0  194.03     .06       0  204.13     .12       0
   279.7    .045       0   295.7     .12       0  322.56    .016       0
  358.96     .12       0
#XS Ineff= 2 , 0
          108.98  456.49
Permanent Ineff=
       F       F
Bank Sta=278.03,291.7
XS Rating Curve= 0 ,0
Exp/Cntr=0.3,0.1

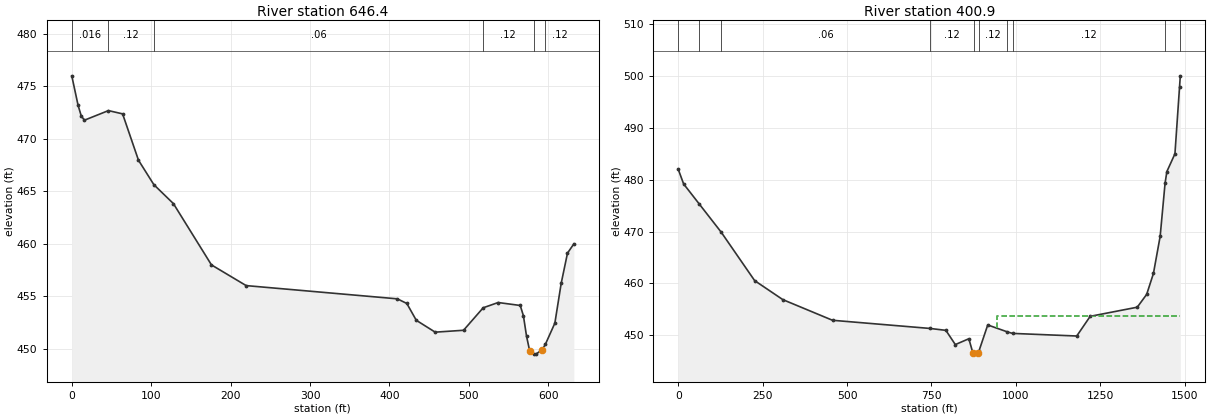
Type RM Length L Ch R = 1 ,646.4   ,244.7,245.5,246.3
XS GIS Cut Line= 3
     2354935.409      422341.242     2355098.175      422274.477
     2355001.876      421828.537
#Sta/Elev= 30
       0  475.99       8  473.17      12  472.16      16  471.77   46.19472.6819
      64  472.37      84  467.96  103.38465.6331     128  463.83   175.9     458
   219.6  456.03     410  454.77   421.9  454.33   433.8  452.73   457.6   451.6
   493.3  451.78  518.07453.9206   536.9  454.42   564.7  454.14   568.7  453.16
   572.6  451.23   576.6  449.81   581.4  449.53   584.5  449.51   592.5  449.94
   596.4  450.45   608.3  452.46   616.3  456.26   624.2  459.12   632.2     460
#Mann= 6 ,-1 , 0
       0    .016       0   46.19     .12       0  103.38     .06       0
  518.07     .12       0   581.4    .045       0   596.4     .12       0
Bank Sta=576.6,592.5
XS Rating Curve= 0 ,0
Exp/Cntr=0.3,0.1

Type RM Length L Ch R = 1 ,400.9   ,387.1,400.9,414.6
XS GIS Cut Line= 4
     2354944.347      422496.537     2355316.114      422326.093
     2355190.981       421617.67     2354839.131      421548.537
#Sta/Elev= 30
       0     482    15.9  479.18   61.15475.4008  127.16469.8891   226.3  460.55
   309.7  456.89   456.9  452.91  746.58451.3324   792.6  450.97   820.6  448.23
   860.6  449.35   872.6  446.63   875.4  446.46   876.6  446.39   888.6   446.7
   890.4  446.95   916.6  452.01  973.28450.7066  990.04450.3831  1180.2  449.88
    1220  453.67  1359.4  455.43  1387.3   457.9  1407.3  461.93  1427.2  469.07
 1441.74479.2912  1447.1  481.56    1471  484.98 1484.68497.9224  1486.9     500
#Mann= 10 ,-1 , 0
       0     .06       0   61.15     .12       0  127.16     .06       0
  746.58     .12       0   875.4    .045       0   890.4     .12       0
  973.28     .06       0  990.04     .12       0 1441.74    .016       0
 1484.68     .12       0
#XS Ineff= 2 , 0
                             943          453.65
Permanent Ineff=
       F       F
Bank Sta=872.6,888.6
XS Rating Curve= 0 ,0
Exp/Cntr=0.3,0.1
LCMann Table=0

Chan Stop Cuts=-1
Use User Specified Reach Order=0
Composite Channel Slope=5